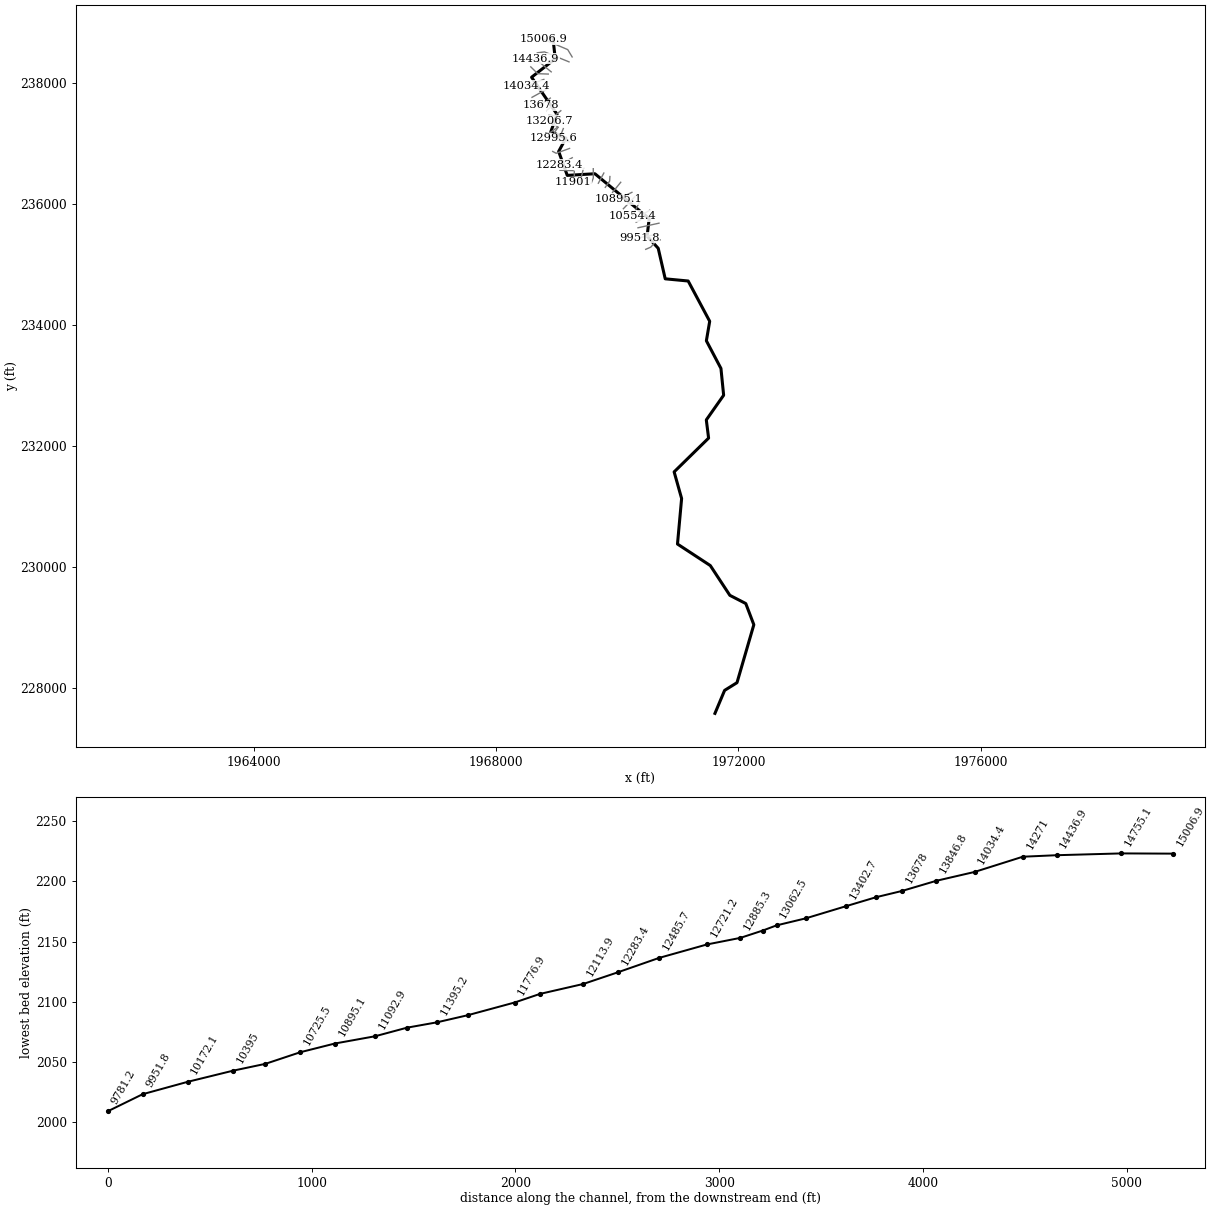
--- PRKRCK.prj (project) ---

Proj Title=PRKRCK
Current Plan=p01
Default Exp/Contr=0,0
English Units
Geom File=g01
Flow File=f01
Plan File=p01
BEGIN DESCRIPTION:
END DESCRIPTION:
DSS Export Rating Curves= 0
DSS Export Rating Curve Sorted= 0
DSS Export Volume Flow Curves= 0
DXF OffsetX= 0
DXF OffsetY= 0
DXF ScaleX= 0
DXF ScaleY= 0

--- PRKRCK.p01 (plan) ---

Plan Title=Floodplain
Program Version=4.00
Geom File=g01
Flow File=f01
K Sum by GR=0
Std Step Tol=0.01
Critical Tol=0.01
Num of Std Step Trials=20
Max Error Tol=0.3
Flow Tol Ratio=0.001
Split Flow NTrial=30
Split Flow Tol=0.02
Split Flow Ratio=0.02
Log Output Level=0
Friction Slope Method=1
Unsteady Friction Slope Method=2
Unsteady Bridges Friction Slope Method=1
Global Log Level=0
CheckData=False
Run HTab=0
Run UNet=0
Run PostProcess=0
UNET Theta=0
UNET Theta Warmup=0
UNET ZTol=0
UNET ZSATol=0
UNET MxIter=0
UNET MaxInSteps=0
UNET DtIC=0
UNET DtMin=0
UNET MaxCRTS=0
UNET WFStab=0
UNET SFStab=0
UNET WFX=0
UNET SFX=0
UNET DSS MLevel=0
UNET DZMax Abort=0
UNET Convert EG Bridges=0
UNET Use Existing IB Tables=0
UNET Froude Limit=0
UNET Froude Power=0
Write IC File=0
Echo Input=False
Echo Output=False
Write Detailed=0

--- PRKRCK.f01 (steady flow) ---

Flow Title=2010 USGS WV Regression Equation
Program Version=4.00
Number of Profiles=1
Profile Names=P100yr
River Rch & RM=PRKRCK,Main      ,15006.9
685.7028
River Rch & RM=PRKRCK,Main      ,12885.3
714.7282
River Rch & RM=PRKRCK,Main      ,11546.5
793.6594
River Rch & RM=PRKRCK,Main      ,7061.7
881.0124
River Rch & RM=PRKRCK,Main      ,4533.8
978.7925
River Rch & RM=PRKRCK,Main      ,1847.8
1013.807
River Rch & RM=PRKRCK,Main      ,1698.6
2018.393
River Rch & RM=PRKRCK,Main      ,289.1
2049.687
Boundary for River Rch & Prof#=PRKRCK,Main      ,1
Up Type=0
Dn Type=3
Dn Slope=0.025379

--- PRKRCK.g01 (geometry) ---

Geom Title=LiDAR
Program Version=4.10

River Reach=PRKRCK          ,Main
Reach XY= 30
     1968935.518      238730.048     1968973.094      238393.723
     1968581.853      238087.425     1969003.165      237475.171
     1968898.971      237185.121     1969149.214      237082.564
     1969029.458      236862.385     1969171.501       236467.09
     1969628.381       236494.37     1970524.908      235753.397
     1970490.881      235463.814     1970674.458      235263.223
     1970790.186      234759.647     1971169.353      234723.536
     1971525.031      234058.366     1971470.047       233736.73
     1971710.868      233280.191     1971755.464      232837.425
     1971468.982      232430.048     1971506.853      232129.786
     1970937.408      231572.147     1971061.019      231132.564
       1970992.8      230380.515     1971535.151      230025.272
     1971858.068      229533.953     1972121.089      229398.536
     1972254.332      229048.679     1971976.124      228092.112
     1971771.263      227964.508     1971611.868         227585.

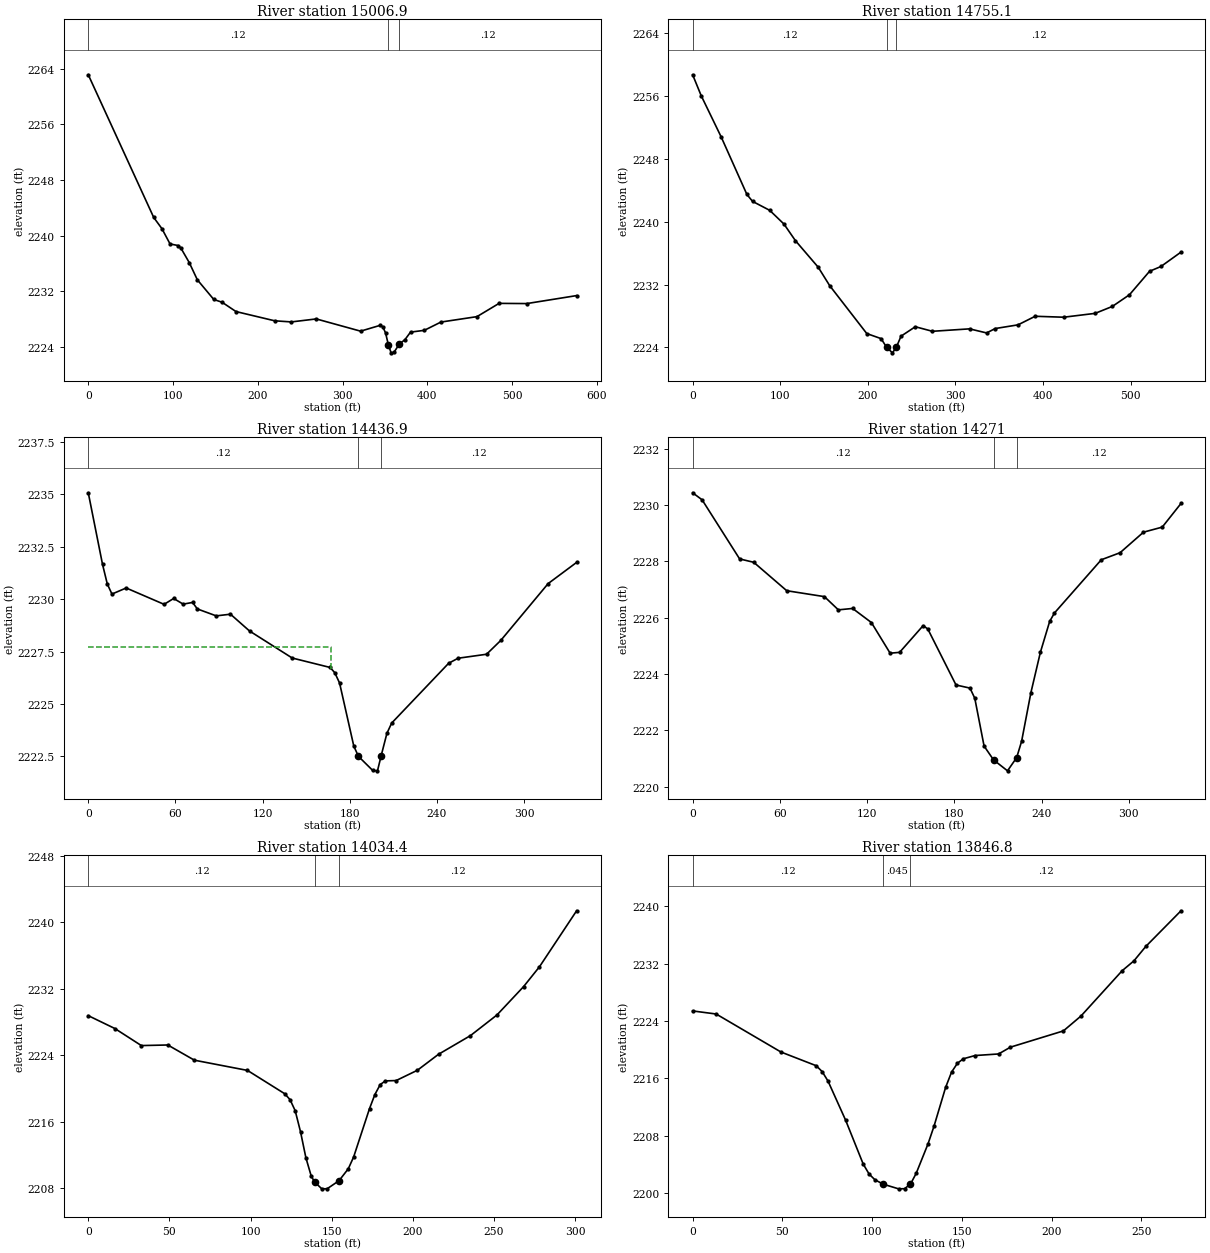
Type RM Length L Ch R = 1 ,15006.9 ,250,251.9,251.4
XS GIS Cut Line= 3
     1969252.461      238422.967     1969179.123      238544.086
     1968779.095      238714.098
#Sta/Elev= 30
       0 2263.14    77.2 2242.61    86.9 2240.99    96.5 2238.79   106.2 2238.56
   109.4 2238.17   119.1 2236.12   128.7 2233.63   148.1  2230.8   157.9  2230.4
   174.3 2229.06     220 2227.73   239.6 2227.57     269    2228   321.3 2226.24
   344.2 2227.07   347.5 2226.87   350.8 2225.98     354 2224.31   357.3 2223.12
   360.6 2223.17   367.1  2224.4   373.6 2225.01   380.2  2226.1   396.5 2226.36
   416.1 2227.55   458.6 2228.33   484.7 2230.24   517.4 2230.21   576.2 2231.36
#Mann= 3 ,-1 , 0
       0     .12       0     354    .045       0   367.1     .12       0
Bank Sta=354,367.1
XS Rating Curve= 0 ,0
Exp/Cntr=0.3,0.1

Type RM Length L Ch R = 1 ,14755.1 ,324.9,318.1,310.9
XS GIS Cut Line= 3
     1969200.721       238341.43     1968796.249      238505.885
     1968676.241       238491.44
#Sta/Elev= 30
       0 2258.67     9.8    2256    32.6 2250.76    61.9 2243.46    68.4 2242.57
      88 2241.43   104.3 2239.68   117.3 2237.58   143.4 2234.19   156.4 2231.86
   198.8 2225.76   215.1 2225.12   221.6 2223.99   228.1 2223.31   232.5 2224.01
   237.9 2225.43   254.2 2226.63   273.7 2226.05   316.1 2226.36   335.6 2225.84
   345.4  2226.4   371.5 2226.87     391 2227.96   423.6 2227.84   459.5 2228.33
   479.1 2229.21   498.7  2230.7   521.6 2233.68   534.6 2234.29   557.5 2236.12
#Mann= 3 ,-1 , 0
       0     .12       0   221.6    .045       0   232.5     .12       0
Bank Sta=221.6,232.5
XS Rating Curve= 0 ,0
Exp/Cntr=0.3,0.1

Type RM Length L Ch R = 1 ,14436.9 ,167.7,165.9,164.1
XS GIS Cut Line= 2
     1968906.233      238176.224     1968647.327      238390.683
#Sta/Elev= 30
       0 2235.07     9.8 2231.66    13.1 2230.72    16.3 2230.24    26.1 2230.53
    52.2 2229.75    58.8 2230.03    65.3 2229.76    71.8 2229.84    75.1 2229.53
    88.1  2229.2    97.9 2229.28     111 2228.48   140.4 2227.19   166.5 2226.74
   169.7 2226.49     173    2226   182.8 2222.99     186  2222.5   195.8 2221.83
   199.1 2221.81  201.67 2222.54   205.6  2223.6   208.9 2224.09   248.1 2226.94
   254.6 2227.18   274.2 2227.37     284 2228.03   316.6 2230.74   336.2 2231.75
#Mann= 3 ,-1 , 0
       0     .12       0     186    .045       0  201.67     .12       0
#XS Ineff= 2 , 0
          167.23  2227.7
Permanent Ineff=
       F       F
Bank Sta=186,201.67
XS Rating Curve= 0 ,0
Exp/Cntr=0.3,0.1

Type RM Length L Ch R = 1 ,14271   ,209.8,236.6,261.7
XS GIS Cut Line= 3
     1968858.084      238140.173     1968683.564      238146.333
     1968568.586      238259.257
#Sta/Elev= 30
       0 2230.44     6.5 2230.19    32.3 2228.09      42 2227.97    64.7 2226.96
    90.6 2226.75   100.2 2226.28     110 2226.33   122.9 2225.83   135.8 2224.74
   142.3 2224.77   158.5 2225.72   161.7  2225.6   181.1 2223.61   190.7  2223.5
     194 2223.14   200.4 2221.44   206.9 2220.95   216.5 2220.56   222.8 2221.03
   226.2 2221.61   232.6 2223.34   239.1 2224.77   245.5 2225.87   248.8 2226.17
     281 2228.06   293.9 2228.31     310 2229.04   322.9 2229.22   335.8 2230.06
#Mann= 3 ,-1 , 0
       0     .12       0   206.9    .045       0   222.8     .12       0
Bank Sta=206.9,222.8
XS Rating Curve= 0 ,0
Exp/Cntr=0.3,0.1

Type RM Length L Ch R = 1 ,14034.4 ,184.3,187.7,190.7
XS GIS Cut Line= 2
      1968784.17      238051.887     1968502.885      237945.121
#Sta/Elev= 30
       0 2228.75    16.4  2227.2    32.7 2225.15      49 2225.22    65.4 2223.39
    98.1 2222.16     121 2219.36   124.3 2218.65   127.5 2217.31   130.8 2214.76
   134.1 2211.64   137.4 2209.43   139.5 2208.73   143.9 2207.91   147.2 2207.92
   154.5 2208.89   160.2 2210.32   163.5 2211.74   173.3 2217.57   176.6 2219.26
   179.9 2220.46   183.1  2220.9   189.7 2220.94   202.8 2222.18   215.8  2224.1
   235.5 2226.35   251.8 2228.83   268.2 2232.24     278 2234.63   300.9 2241.37
#Mann= 3 ,-1 , 0
       0     .12       0   139.5    .045       0   154.5     .12       0
Bank Sta=139.5,154.5
XS Rating Curve= 0 ,0
Exp/Cntr=0.3,0.1

Type RM Length L Ch R = 1 ,13846.8 ,165.9,168.8,171.6
XS GIS Cut Line= 2
     1968827.286      237887.633     1968589.118      237756.229
#Sta/Elev= 30
       0 2225.41    13.1 2224.98    49.2 2219.67    68.8 2217.76    72.1 2216.95
    75.4 2215.61    85.2 2210.15      95 2204.02    98.3 2202.62   101.6 2201.81
  106.29  2201.2   114.7 2200.56     118 2200.58   121.3 2201.21   124.5 2202.72
   131.1 2206.84   134.4 2209.28   140.9 2214.73   144.2 2216.86   147.5 2218.11
   150.8 2218.73   157.3 2219.18   170.4  2219.4     177 2220.35   206.5 2222.62
   216.3  2224.7   239.2 2231.02   245.8 2232.41   252.4 2234.42     272  2239.4
#Mann= 3 ,-1 , 0
       0     .12       0  106.29    .045       0   121.3     .12       0
Bank Sta=106.29,121.3
XS Rating Curve= 0 ,0
Exp/Cntr=0.3,0.1

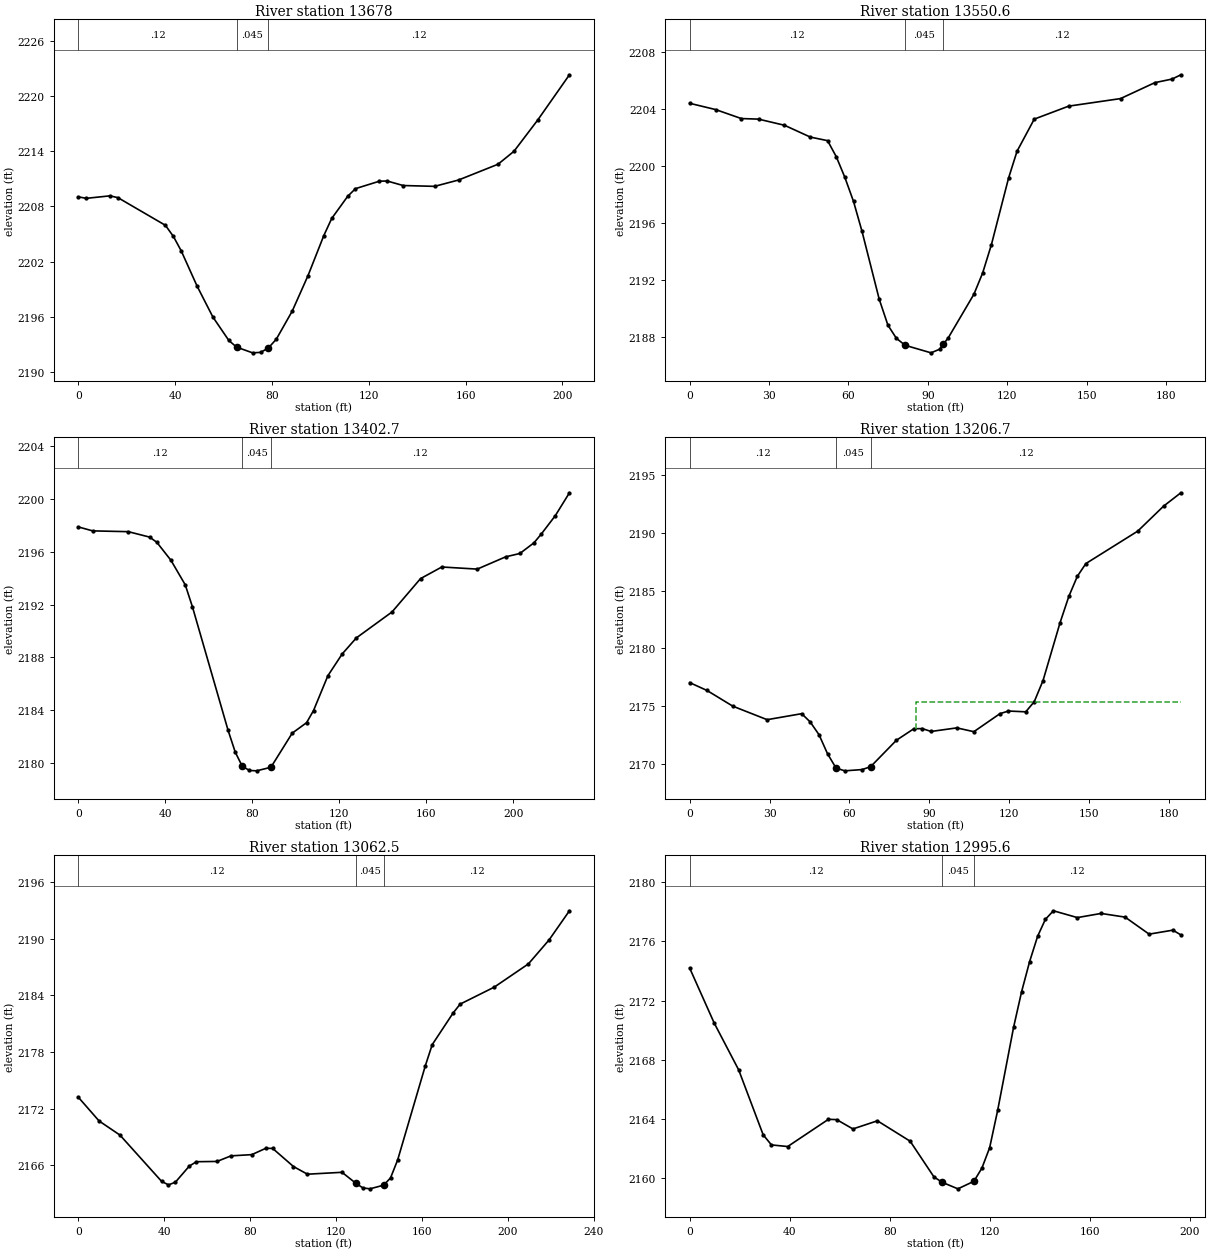
Type RM Length L Ch R = 1 ,13678   ,126.9,127.4,127.9
XS GIS Cut Line= 2
     1968890.935       237743.91     1968726.681      237624.826
#Sta/Elev= 30
       0 2209.04     3.3 2208.88    13.1 2209.15    16.4 2208.95      36 2205.95
    39.3 2204.74    42.5 2203.19    49.1 2199.34    55.6    2196    62.2 2193.45
    65.4 2192.73      72 2192.11    75.3 2192.16    78.5 2192.63    81.8 2193.59
    88.4 2196.65    94.9 2200.49   101.4 2204.82   104.7  2206.7   111.3  2209.1
   114.5 2209.93   124.4 2210.74   127.6 2210.76   134.2 2210.27   147.2 2210.18
   157.1 2210.87   173.4 2212.58     180 2213.99   189.8 2217.38   202.9 2222.29
#Mann= 3 ,-1 , 0
       0     .12       0    65.4    .045       0    78.5     .12       0
Bank Sta=65.4,78.5
XS Rating Curve= 0 ,0
Exp/Cntr=0.3,0.1

Type RM Length L Ch R = 1 ,13550.6 ,147.4,147.9,148.3
XS GIS Cut Line= 2
     1968978.483      237652.494     1968830.696      237540.264
#Sta/Elev= 30
       0 2204.41     9.8 2203.97    19.5 2203.34      26  2203.3    35.8 2202.87
    45.6 2202.04    52.1 2201.79    55.4 2200.66    58.6 2199.23    61.9 2197.53
    65.1 2195.44    71.6 2190.68    74.9 2188.85    78.1 2187.93    81.4 2187.44
    91.2 2186.91    94.4 2187.16   95.77  2187.5    97.7 2187.96   107.4 2191.02
   110.7 2192.51     114 2194.49   120.5 2199.17   123.7 2201.05   130.2  2203.3
   143.2 2204.21   162.8 2204.74   175.8 2205.86   182.3 2206.11   185.6 2206.41
#Mann= 3 ,-1 , 0
       0     .12       0    81.4    .045       0   95.77     .12       0
Bank Sta=81.4,95.77
XS Rating Curve= 0 ,0
Exp/Cntr=0.3,0.1

Type RM Length L Ch R = 1 ,13402.7 ,224.3,196,166.4
XS GIS Cut Line= 3
     1969065.156      237534.708     1968959.593      237451.369
     1968868.476      237459.147
#Sta/Elev= 30
       0 2197.87     6.6 2197.57      23 2197.51    32.8  2197.1    36.1 2196.71
    42.6 2195.35    49.2 2193.49    52.5 2191.83    68.9 2182.49    72.2 2180.84
    75.4 2179.78    78.7 2179.46      82 2179.43    88.6  2179.7    98.4 2182.28
     105 2183.07   108.2 2183.99   114.8 2186.62   121.4 2188.27   127.9 2189.48
   144.3 2191.44   157.4 2193.96   167.2 2194.84   183.5 2194.68   196.6 2195.61
   203.1 2195.86   209.6 2196.67   212.9 2197.32   219.4 2198.72   225.9 2200.45
#Mann= 3 ,-1 , 0
       0     .12       0    75.4    .045       0    88.6     .12       0
Bank Sta=75.4,88.6
XS Rating Curve= 0 ,0
Exp/Cntr=0.3,0.1

Type RM Length L Ch R = 1 ,13206.7 ,114.5,144.3,171.7
XS GIS Cut Line= 2
     1969022.251      237262.398     1968870.252      237367.078
#Sta/Elev= 30
       0 2177.04     6.5 2176.36    16.2    2175    29.1 2173.83    42.1 2174.35
    45.3 2173.63    48.6 2172.53    51.8 2170.88      55 2169.64    58.3  2169.4
    64.8 2169.51      68 2169.76    77.7 2172.05    84.2 2173.04    87.4 2173.06
    90.7 2172.81   100.4 2173.12   106.8 2172.79   116.6 2174.35   119.8 2174.58
   126.3 2174.51   129.5 2175.39   132.8 2177.22   139.2 2182.23   142.5 2184.51
   145.7 2186.25   148.9 2187.35   168.4 2190.16   178.1 2192.32   184.6 2193.48
#Mann= 3 ,-1 , 0
       0     .12       0      55    .045       0      68     .12       0
#XS Ineff= 2 , 0
                           85.04         2175.39
Permanent Ineff=
       F       F
Bank Sta=55,68
XS Rating Curve= 0 ,0
Exp/Cntr=0.3,0.1

Type RM Length L Ch R = 1 ,13062.5 ,51.7,66.9,84
XS GIS Cut Line= 3
       1969009.9      237261.884     1968863.372      237155.634
     1968817.539      237168.829
#Sta/Elev= 30
       0 2173.22     9.7  2170.7    19.4 2169.21    38.8 2164.31      42 2163.94
    45.2 2164.22    51.7 2165.93      55 2166.39    64.6 2166.42    71.1 2167.01
    80.8 2167.14    87.3 2167.81    90.5  2167.8   100.2 2165.88   106.7 2165.07
   122.8 2165.27   129.3  2164.1   132.5 2163.62   135.8 2163.52   142.2 2163.91
   145.4 2164.68   148.7 2166.57   161.6 2176.55   164.8 2178.78   174.5 2182.12
   177.8 2183.07   193.7 2184.87   209.6 2187.33   219.2 2189.86   228.7 2192.95
#Mann= 3 ,-1 , 0
       0     .12       0   129.3    .045       0   142.2     .12       0
Bank Sta=129.3,142.2
XS Rating Curve= 0 ,0
Exp/Cntr=0.3,0.1

Type RM Length L Ch R = 1 ,12995.6 ,111.9,110.3,105.8
XS GIS Cut Line= 3
     1969016.497      237256.476     1968966.584      237183.776
     1968945.968       237077.44
#Sta/Elev= 30
       0 2174.19     9.8 2170.48    19.6 2167.31    29.4 2162.92    32.7 2162.24
    39.2 2162.13    55.5 2163.97    58.8 2163.95    65.3 2163.32    75.1 2163.87
    88.2 2162.49    97.7 2160.08   100.9 2159.72   107.3 2159.27   113.7 2159.78
   116.9 2160.67     120 2162.05   123.2 2164.57   129.6 2170.21   132.8 2172.61
     136 2174.64   139.2 2176.35   142.3 2177.49   145.5 2178.07   155.1 2177.61
   164.6 2177.89   174.2 2177.64   183.8 2176.49   193.3 2176.76   196.5 2176.44
#Mann= 3 ,-1 , 0
       0     .12       0   100.9    .045       0   113.7     .12       0
Bank Sta=100.9,113.7
XS Rating Curve= 0 ,0
Exp/Cntr=0.3,0.1

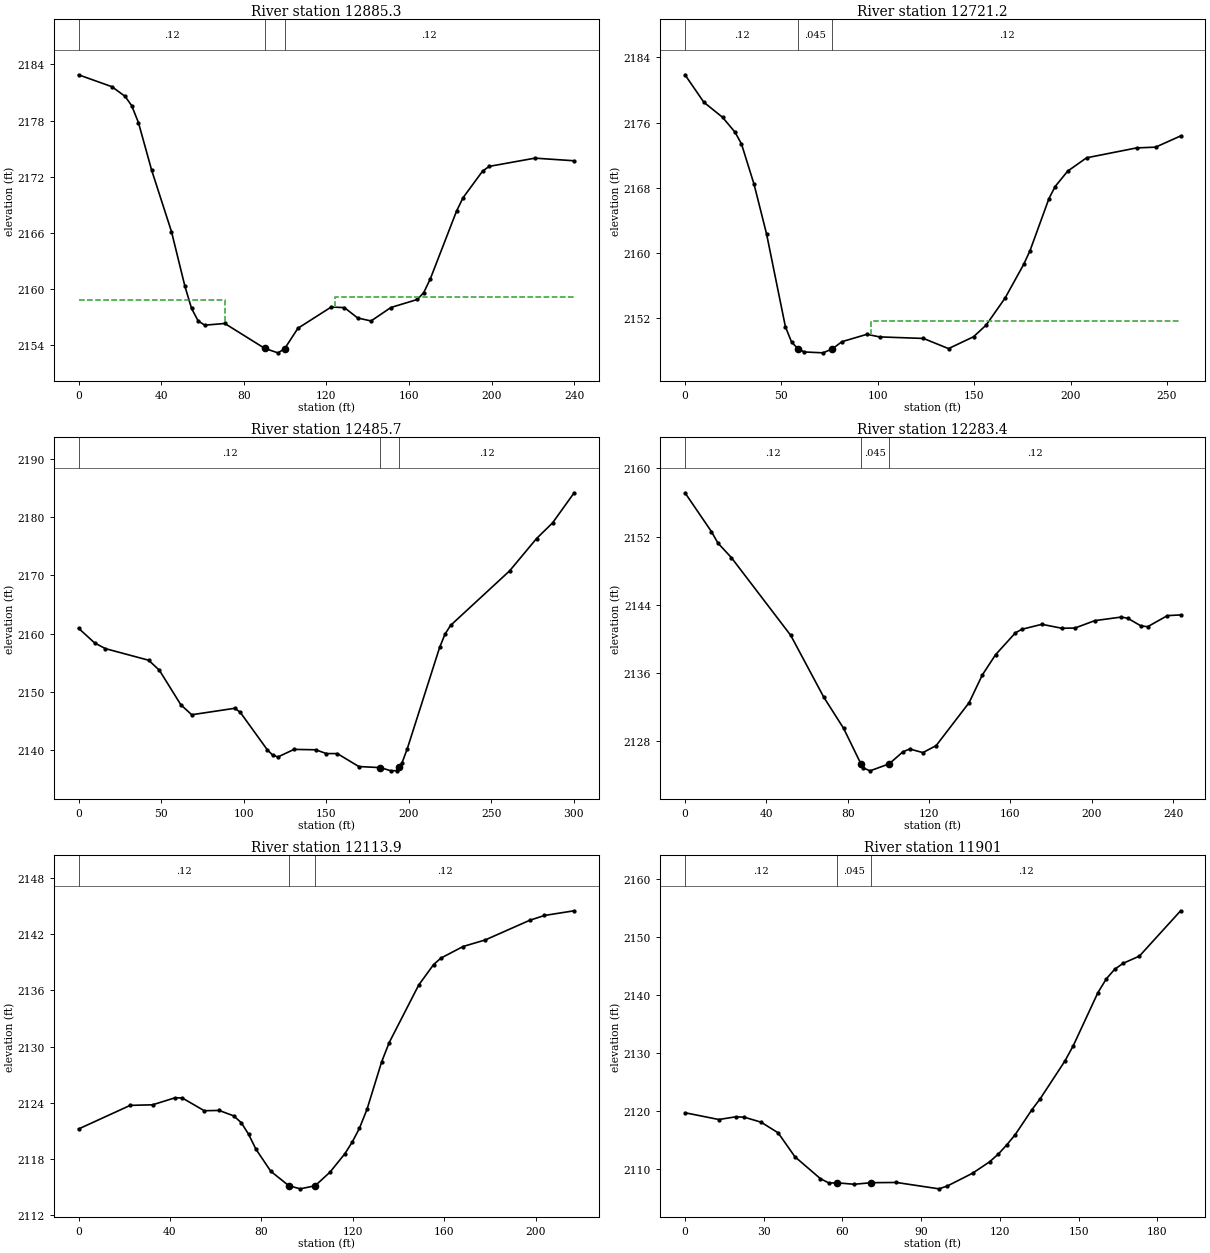
Type RM Length L Ch R = 1 ,12885.3 ,194.3,164.1,133.3
XS GIS Cut Line= 3
      1969106.27      237240.243     1969048.488      237093.567
     1968970.705      237066.898
#Sta/Elev= 30
       0  2182.9    16.1 2181.63    22.5  2180.6    25.7 2179.61      29 2177.79
    35.4 2172.69      45 2166.12    51.5 2160.27    54.7 2157.91    57.9 2156.57
    61.1 2156.11    70.8 2156.29    90.1 2153.63    96.5 2153.15    99.7 2153.57
   106.2 2155.78   122.3 2158.05   128.7 2157.99   135.1 2156.88   141.6 2156.56
   151.2    2158     164 2158.86   167.1  2159.6   170.3 2161.08     183 2168.33
   186.1 2169.74   195.6  2172.6   198.8  2173.1   220.9 2173.98   239.9  2173.7
#Mann= 3 ,-1 , 0
       0     .12       0    90.1    .045       0    99.7     .12       0
#XS Ineff= 2 , 0
           70.95 2158.81   124.1         2159.16
Permanent Ineff=
       F       F
Bank Sta=90.1,99.7
XS Rating Curve= 0 ,0
Exp/Cntr=0.3,0.1

Type RM Length L Ch R = 1 ,12721.2 ,222.7,235.4,246
XS GIS Cut Line= 2
       1969218.5      237019.117     1968964.038      237055.786
#Sta/Elev= 30
       0 2181.87     9.8 2178.49    19.5 2176.64      26  2174.8    29.3 2173.37
    35.8 2168.43    42.3 2162.32    52.1 2150.88    55.3    2149    58.6 2148.19
    61.8 2147.79    71.6 2147.68    76.4 2148.16    81.4 2149.05    94.4 2149.96
   100.9 2149.64   123.7 2149.45   136.7  2148.2   149.7 2149.66   156.2 2151.09
     166  2154.4   175.7 2158.56     179 2160.26   188.8 2166.65     192 2168.13
   198.5 2170.02   208.3 2171.66   234.3 2172.88   244.1 2172.97   257.1 2174.35
#Mann= 3 ,-1 , 0
       0     .12       0    58.6    .045       0    76.4     .12       0
#XS Ineff= 2 , 0
                           96.28         2151.55
Permanent Ineff=
       F       F
Bank Sta=58.6,76.4
XS Rating Curve= 0 ,0
Exp/Cntr=0.3,0.1

Type RM Length L Ch R = 1 ,12485.7 ,198.4,202.3,205.2
XS GIS Cut Line= 3
      1969209.61      236912.443     1968988.484      236832.438
     1968930.702       236862.44
#Sta/Elev= 30
       0 2160.94     9.8 2158.41    16.3 2157.44    42.5 2155.45      49 2153.73
      62 2147.81    68.6  2146.1    94.7 2147.21      98 2146.52   114.3 2140.12
   117.6 2139.19   120.8 2138.86   130.6 2140.16   143.7 2140.09   150.2 2139.44
   156.8 2139.44   169.8 2137.22   182.9 2137.03   189.4 2136.48   192.7 2136.52
  194.07 2137.07     196 2137.85   199.2 2140.28   218.8 2157.66   222.1 2159.95
   225.4 2161.42   261.2 2170.78   277.5 2176.32   287.2    2179   300.3 2184.17
#Mann= 3 ,-1 , 0
       0     .12       0   182.9    .045       0  194.07     .12       0
Bank Sta=182.9,194.07
XS Rating Curve= 0 ,0
Exp/Cntr=0.3,0.1

Type RM Length L Ch R = 1 ,12283.4 ,181.3,169.5,157.2
XS GIS Cut Line= 2
     1969254.058      236759.099      1969040.71      236641.313
#Sta/Elev= 30
       0 2157.14      13 2152.59    16.2 2151.24    22.8 2149.54      52 2140.41
    68.2 2133.18      78  2129.5   86.47 2125.36    87.7 2124.86      91 2124.52
   100.4 2125.34   107.2 2126.76   110.5 2127.08     117 2126.66   123.5 2127.48
   139.7 2132.52   146.2 2135.77   152.7 2138.14   162.5 2140.72   165.7 2141.13
   175.5 2141.71   185.2 2141.25   191.7 2141.27   201.5 2142.14   214.5 2142.56
   217.7 2142.42   224.2 2141.52   227.5 2141.43   237.2 2142.73   243.7 2142.81
#Mann= 3 ,-1 , 0
       0     .12       0   86.47    .045       0   100.4     .12       0
Bank Sta=86.47,100.4
XS Rating Curve= 0 ,0
Exp/Cntr=0.3,0.1

Type RM Length L Ch R = 1 ,12113.9 ,173.9,212.9,248.9
XS GIS Cut Line= 2
     1969267.392      236545.751     1969050.711      236551.307
#Sta/Elev= 30
       0 2121.22    22.6 2123.74    32.4  2123.8    42.1 2124.54    45.3 2124.54
      55 2123.17    61.5  2123.2    67.9 2122.62    71.2 2121.89    74.4 2120.66
    77.6 2119.07    84.1 2116.71   92.02 2115.17      97 2114.84   103.5 2115.17
     110 2116.62   116.5 2118.58   119.7 2119.82   122.9 2121.31   126.2 2123.33
   132.6 2128.39   135.9 2130.44   148.8 2136.57   155.3 2138.75   158.5 2139.44
   168.2 2140.68   177.9 2141.38   197.3 2143.47   203.8 2143.99   216.8 2144.49
#Mann= 3 ,-1 , 0
       0     .12       0   92.02    .045       0   103.5     .12       0
Bank Sta=92.02,103.5
XS Rating Curve= 0 ,0
Exp/Cntr=0.3,0.1

Type RM Length L Ch R = 1 ,11901   ,128.8,124.1,117.4
XS GIS Cut Line= 3
     1969287.393      236534.639     1969289.616      236402.408
      1969265.17      236351.294
#Sta/Elev= 30
       0 2119.71    12.9 2118.54    19.4 2119.01    22.6 2118.94      29 2118.08
    35.5 2116.24    41.9 2112.11    51.6 2108.33    54.8 2107.59    58.1  2107.6
    64.5 2107.36      71 2107.63    80.6 2107.67    96.8 2106.57     100 2107.06
   109.7 2109.29   116.1 2111.24   119.4 2112.56   122.6 2114.14   125.8 2115.89
   132.2 2120.22   135.4 2122.14   144.8 2128.64     148  2131.3   157.4 2140.47
   160.6 2142.84   163.7 2144.45   166.9 2145.49   173.2 2146.76   188.9 2154.58
#Mann= 3 ,-1 , 0
       0     .12       0    58.1    .045       0      71     .12       0
Bank Sta=58.1,71
XS Rating Curve= 0 ,0
Exp/Cntr=0.3,0.1

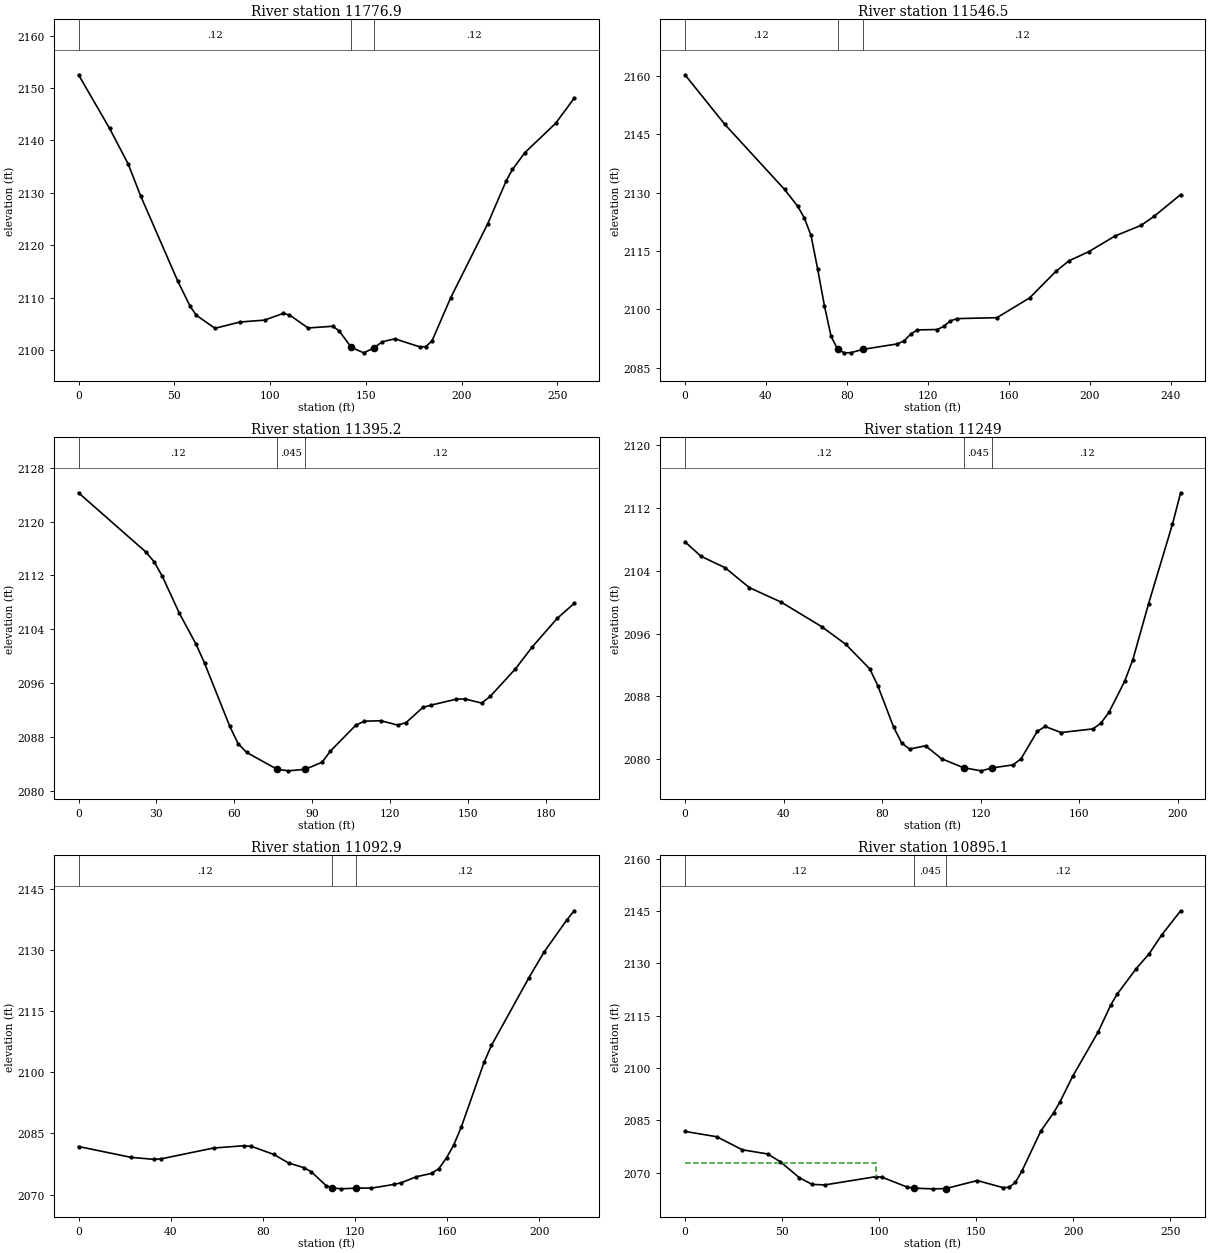
Type RM Length L Ch R = 1 ,11776.9 ,224.6,230.3,235.1
XS GIS Cut Line= 3
     1969439.132      236583.867     1969390.734      236382.407
     1969384.067      236331.292
#Sta/Elev= 30
       0 2152.53    16.2  2142.3    25.9 2135.52    32.4 2129.43    51.8 2113.14
    58.3  2108.3    61.5 2106.62    71.2 2104.12    84.2 2105.32    97.1 2105.69
   106.8 2106.96   110.1 2106.68   119.8 2104.19   132.7 2104.51     136 2103.64
   142.4 2100.48   148.9 2099.44     154 2100.35   158.6 2101.56   165.1 2102.12
   178.1 2100.58   181.3 2100.64   184.5 2101.71   194.2 2109.92   213.6  2124.1
   223.3 2132.33   226.5 2134.46     233 2137.67   249.1 2143.29   258.7 2148.06
#Mann= 3 ,-1 , 0
       0     .12       0   142.4    .045       0     154     .12       0
Bank Sta=142.4,154
XS Rating Curve= 0 ,0
Exp/Cntr=0.3,0.1

Type RM Length L Ch R = 1 ,11546.5 ,162.7,151.4,139.9
XS GIS Cut Line= 3
     1969601.333      236577.707     1969601.859      236423.521
     1969568.524      236339.071
#Sta/Elev= 30
       0  2160.2    19.7 2147.48    49.2  2130.8    55.8 2126.42      59 2123.47
    62.3 2118.99    65.6 2110.32    68.9 2101.02    72.2 2093.14    75.4 2089.87
    78.7 2088.88      82 2088.92    88.1 2089.79     105 2091.17   108.3 2091.95
   111.5 2093.64   114.8 2094.76   124.7 2094.86   127.9 2095.66   131.2 2097.07
   134.5 2097.66   154.2  2097.9   170.4 2102.99   183.4 2109.82   189.9 2112.51
   199.6 2114.83   212.6 2118.86   225.5 2121.59     232 2123.94     245 2129.47
#Mann= 3 ,-1 , 0
       0     .12       0    75.4    .045       0    88.1     .12       0
Bank Sta=75.4,88.1
XS Rating Curve= 0 ,0
Exp/Cntr=0.3,0.1

Type RM Length L Ch R = 1 ,11395.2 ,148.6,146.1,143.4
XS GIS Cut Line= 2
     1969775.853      236505.846     1969685.198      236337.959
#Sta/Elev= 30
       0 2124.29    25.9  2115.5    29.1 2114.04    32.3 2111.85    38.8  2106.4
    45.3 2101.75    48.5 2098.99    58.2 2089.61    61.4 2087.03    64.7 2085.71
   76.46  2083.2    80.8 2082.97    87.3  2083.2    93.8 2084.26      97 2085.92
   106.7 2089.74     110 2090.34   116.4 2090.42   122.9 2089.76   126.1 2090.14
   132.6 2092.41   135.8 2092.74   145.5 2093.63   148.8 2093.65   155.2 2093.04
   158.5 2094.04   168.2 2098.13   174.6 2101.35   184.3 2105.64   190.8 2107.85
#Mann= 3 ,-1 , 0
       0     .12       0   76.46    .045       0    87.3     .12       0
Bank Sta=76.46,87.3
XS Rating Curve= 0 ,0
Exp/Cntr=0.3,0.1

Type RM Length L Ch R = 1 ,11249   ,157.4,156.1,154.2
XS GIS Cut Line= 3
     1969876.459      236448.357     1969871.878      236373.517
     1969799.651      236270.177
#Sta/Elev= 30
       0 2107.66     6.5 2105.82    16.3 2104.36    26.1 2101.84    39.1 2099.98
    55.4 2096.89    65.2 2094.64      75  2091.5    78.2 2089.39    84.7 2084.07
    87.9  2082.1    91.1 2081.32    97.6 2081.73   104.1 2080.09  113.01 2078.95
   120.2 2078.55   124.7 2078.93   133.2 2079.31   136.4 2080.11   142.9 2083.55
   146.1 2084.19   152.6 2083.42   165.5 2083.88   168.7 2084.59     172 2085.98
   178.4 2089.94   181.7 2092.67   188.1  2099.8   197.8 2109.92   201.1 2113.89
#Mann= 3 ,-1 , 0
       0     .12       0  113.01    .045       0   124.7     .12       0
Bank Sta=113.01,124.7
XS Rating Curve= 0 ,0
Exp/Cntr=0.3,0.1

Type RM Length L Ch R = 1 ,11092.9 ,207.1,197.9,187.3
XS GIS Cut Line= 2
     1970055.085      236353.911     1969919.659      236186.838
#Sta/Elev= 30
       0 2081.81    22.8 2079.15    32.6 2078.67    35.8 2078.78    58.6 2081.44
    71.7    2082      75 2081.85    84.7 2079.88    91.2 2077.76    97.8 2076.63
     101 2075.63   107.5 2072.21  110.07 2071.68     114 2071.44   120.6 2071.63
   127.1 2071.62   136.9 2072.52   140.1 2072.95   146.6  2074.4   153.2 2075.23
   156.4 2076.41   159.7 2079.02   162.9 2082.26   166.2 2086.71     176 2102.43
   179.2 2106.57   195.5  2123.2     202 2129.42   211.8 2137.23   215.1 2139.56
#Mann= 3 ,-1 , 0
       0     .12       0  110.07    .045       0   120.6     .12       0
Bank Sta=110.07,120.6
XS Rating Curve= 0 ,0
Exp/Cntr=0.3,0.1

Type RM Length L Ch R = 1 ,10895.1 ,161.5,169.6,177.7
XS GIS Cut Line= 2
      1970239.87      236187.604     1970010.776      236074.608
#Sta/Elev= 30
       0 2081.85    16.4 2080.32    29.5 2076.59    42.6 2075.38    49.1 2073.17
      59 2068.55    65.5 2066.67      72 2066.51    98.2 2068.87   101.5 2068.73
   114.6 2065.87   117.9 2065.58   127.7 2065.39   134.3 2065.45   150.6 2067.77
   163.8 2065.75     167 2065.82   170.3 2067.27   173.6 2070.47   183.4 2081.99
     190 2087.23   193.2 2090.27   199.8 2097.67   212.9 2110.34   219.4 2118.09
   222.7  2121.2   232.5 2128.49   239.1 2132.71   245.6 2138.12   255.4 2145.08
#Mann= 3 ,-1 , 0
       0     .12       0   117.9    .045       0   134.3     .12       0
#XS Ineff= 2 , 0
           98.45 2072.84
Permanent Ineff=
       F       F
Bank Sta=117.9,134.3
XS Rating Curve= 0 ,0
Exp/Cntr=0.3,0.1

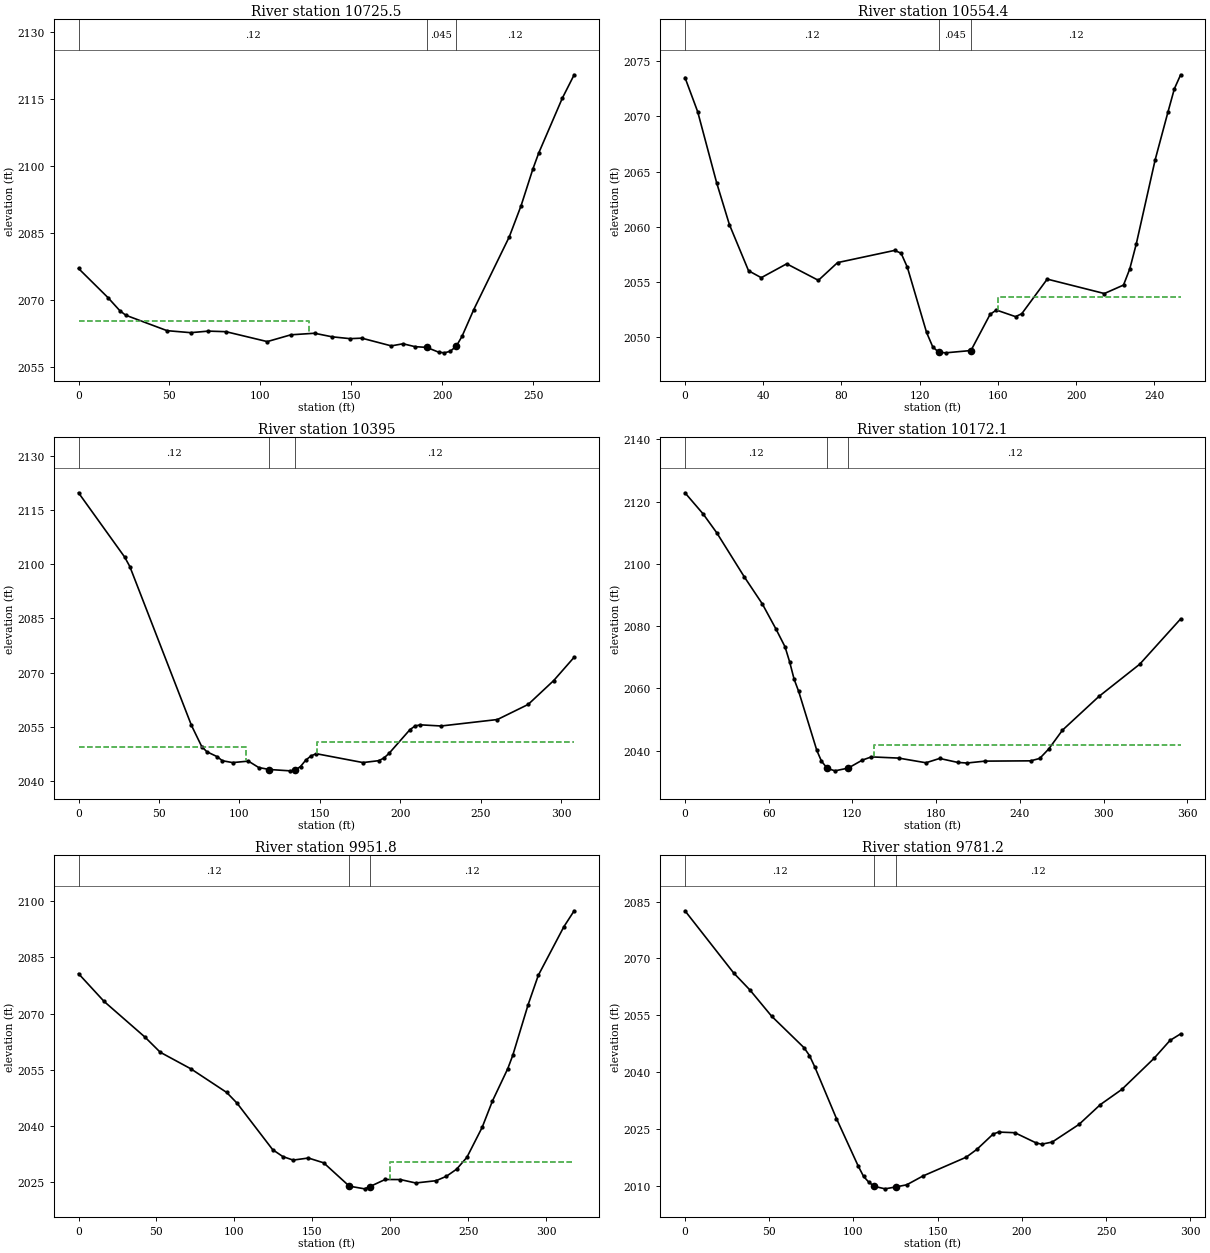
Type RM Length L Ch R = 1 ,10725.5 ,163.5,171.1,177.7
XS GIS Cut Line= 2
     1970287.093       236113.69      1970098.56      235916.819
#Sta/Elev= 30
       0 2077.07    16.2 2070.54    22.7 2067.62      26 2066.59    48.7 2063.13
    61.7 2062.68    71.4 2063.03    81.1  2062.9   103.8 2060.68   116.8  2062.2
   129.8 2062.55   139.5 2061.75   149.3 2061.34   155.8 2061.45     172 2059.72
   178.5 2060.19     185 2059.55   191.5 2059.38     198 2058.32   201.2 2058.16
   204.4 2058.51   207.7 2059.61   210.9 2061.84   217.4 2067.87   236.9 2084.15
   243.4 2091.13   249.9 2099.37   253.1 2102.94   266.1 2115.25   272.6 2120.48
#Mann= 3 ,-1 , 0
       0     .12       0   191.5    .045       0   207.7     .12       0
#XS Ineff= 2 , 0
          126.63 2065.27
Permanent Ineff=
       F       F
Bank Sta=191.5,207.7
XS Rating Curve= 0 ,0
Exp/Cntr=0.3,0.1

Type RM Length L Ch R = 1 ,10554.4 ,161.9,159.4,156.9
XS GIS Cut Line= 2
     1970363.061      236025.403     1970252.189      235797.501
#Sta/Elev= 30
       0 2073.54     6.5 2070.43    16.2 2063.97    22.7 2060.18    32.5 2055.98
      39 2055.35      52 2056.61    68.2 2055.11      78 2056.72   107.2 2057.83
   110.5 2057.57   113.7 2056.29   123.5 2050.38   126.7 2049.05   129.7 2048.58
   133.2 2048.52   146.2 2048.73     156 2052.02   159.2 2052.41     169 2051.81
   172.2 2052.08   185.2 2055.22   214.4 2053.91   224.2 2054.68   227.4 2056.15
   230.7  2058.4   240.4 2066.08   246.9 2070.39   250.2 2072.52   253.4 2073.79
#Mann= 3 ,-1 , 0
       0     .12       0   129.7    .045       0   146.2     .12       0
#XS Ineff= 2 , 0
                          160.06         2053.56
Permanent Ineff=
       F       F
Bank Sta=129.7,146.2
XS Rating Curve= 0 ,0
Exp/Cntr=0.3,0.1

Type RM Length L Ch R = 1 ,10395   ,240.6,222.9,204.9
XS GIS Cut Line= 4
     1970533.474      235891.947     1970456.362      235846.815
     1970383.672      235731.749     1970309.678      235694.842
#Sta/Elev= 30
       0 2119.75    28.7 2101.95    31.9 2099.34    70.2 2055.39    76.6 2049.52
    79.8 2048.09    86.2 2046.73    89.4 2045.61    95.8 2045.09   105.6  2045.5
     112 2043.73   118.6 2043.18   131.5 2042.81   134.7 2043.01     138 2044.01
   141.2 2045.74   144.4  2046.9   147.7 2047.56   176.8  2045.1   186.6 2045.62
   189.8 2046.34     193 2047.63     206  2054.2   209.2 2055.22   212.5 2055.54
   225.4 2055.22   260.4 2057.01   279.5 2061.18   295.4  2067.8   308.1 2074.25
#Mann= 3 ,-1 , 0
       0     .12       0   118.6    .045       0   134.7     .12       0
#XS Ineff= 2 , 0
          104.02 2049.46  148.45         2050.81
Permanent Ineff=
       F       F
Bank Sta=118.6,134.7
XS Rating Curve= 0 ,0
Exp/Cntr=0.3,0.1

Type RM Length L Ch R = 1 ,10172.1 ,220.5,220.3,219
XS GIS Cut Line= 2
     1970687.462      235678.417     1970340.476      235602.449
#Sta/Elev= 30
       0 2122.81      13 2116.02    22.8 2109.95    42.4 2095.89    55.4 2087.15
    65.2 2079.07    71.7 2073.36      75 2068.52    78.2 2062.97    81.5 2059.02
    94.5 2040.08    97.8 2036.66     102 2034.32   107.5 2033.54     117 2034.43
   127.1 2036.99   133.6 2038.02   153.2 2037.63   172.7 2036.13   182.5 2037.52
   195.5 2036.24     202 2036.05   215.1 2036.66   247.7 2036.75   254.2 2037.52
   260.7 2040.57   270.5 2046.59   296.6 2057.41   325.9 2067.78   355.2 2082.32
#Mann= 3 ,-1 , 0
       0     .12       0     102    .045       0     117     .12       0
#XS Ineff= 2 , 0
                           135.4         2041.89
Permanent Ineff=
       F       F
Bank Sta=102,117
XS Rating Curve= 0 ,0
Exp/Cntr=0.3,0.1

Type RM Length L Ch R = 1 ,9951.8  ,155.3,170.7,185.6
XS GIS Cut Line= 2
      1970673.09      235497.737       1970360.8      235439.009
#Sta/Elev= 30
       0 2080.62    16.4 2073.22    42.6 2063.72    52.4 2059.68    72.1 2055.25
      95 2048.97   101.6 2046.14   124.5 2033.72     131 2031.89   137.6 2030.95
   147.4  2031.5   157.2 2030.22   173.6 2024.01   183.4 2023.29   186.7 2023.87
   196.6 2025.78   206.4 2025.76   216.2 2024.85   229.3 2025.46   235.9 2026.64
   242.4 2028.52     249 2031.67   258.8 2039.66   265.4 2046.69   275.2 2055.28
   278.4 2058.82   288.3 2072.38   294.8 2080.17   311.2 2093.12   317.8 2097.37
#Mann= 3 ,-1 , 0
       0     .12       0   173.6    .045       0   186.7     .12       0
#XS Ineff= 2 , 0
                          199.74         2030.54
Permanent Ineff=
       F       F
Bank Sta=173.6,186.7
XS Rating Curve= 0 ,0
Exp/Cntr=0.3,0.1

Type RM Length L Ch R = 1 ,9781.2  ,161.5,150.8,139.9
XS GIS Cut Line= 4
     1970706.864      235402.063     1970639.082      235382.061
     1970552.409      235283.166     1970467.959      235246.496
#Sta/Elev= 30
       0 2082.56    28.9 2066.14    38.6 2061.62    51.4 2054.74    70.7 2046.39
    73.9 2044.33    77.1 2041.28    89.9 2027.71   102.8 2015.18     106 2012.43
   109.2 2010.85   112.4 2009.79   118.8 2009.14   125.2 2009.65   131.6  2010.2
   141.2 2012.52   166.9 2017.49   173.3 2019.58   182.9  2023.6   186.1 2024.13
   195.8 2023.96   208.5 2021.25   211.7 2020.92     218  2021.5   233.9 2026.16
   246.6  2031.4   259.3 2035.39   278.4 2043.59   287.9 2048.33   294.2 2050.06
#Mann= 3 ,-1 , 0
       0     .12       0   112.4    .045       0   125.2     .12       0
Bank Sta=112.4,125.2
XS Rating Curve= 0 ,0
Exp/Cntr=0.3,0.1