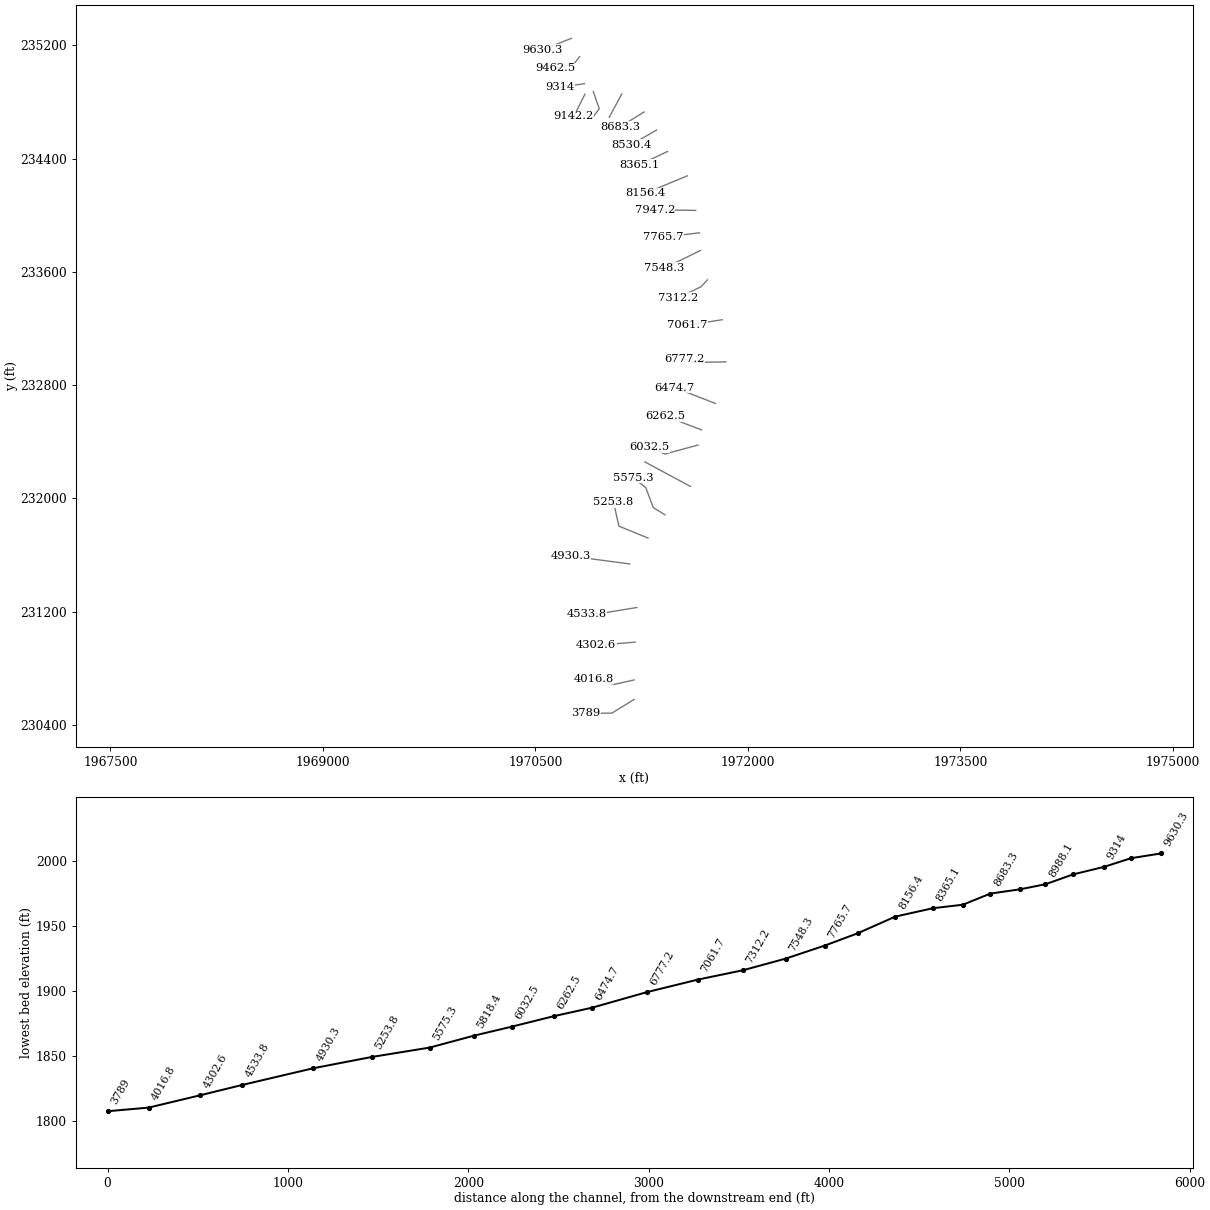
HEC-RAS study PRKRCK.prj: PRKRCK

--- PRKRCK.g01 (geometry) --- (continued)

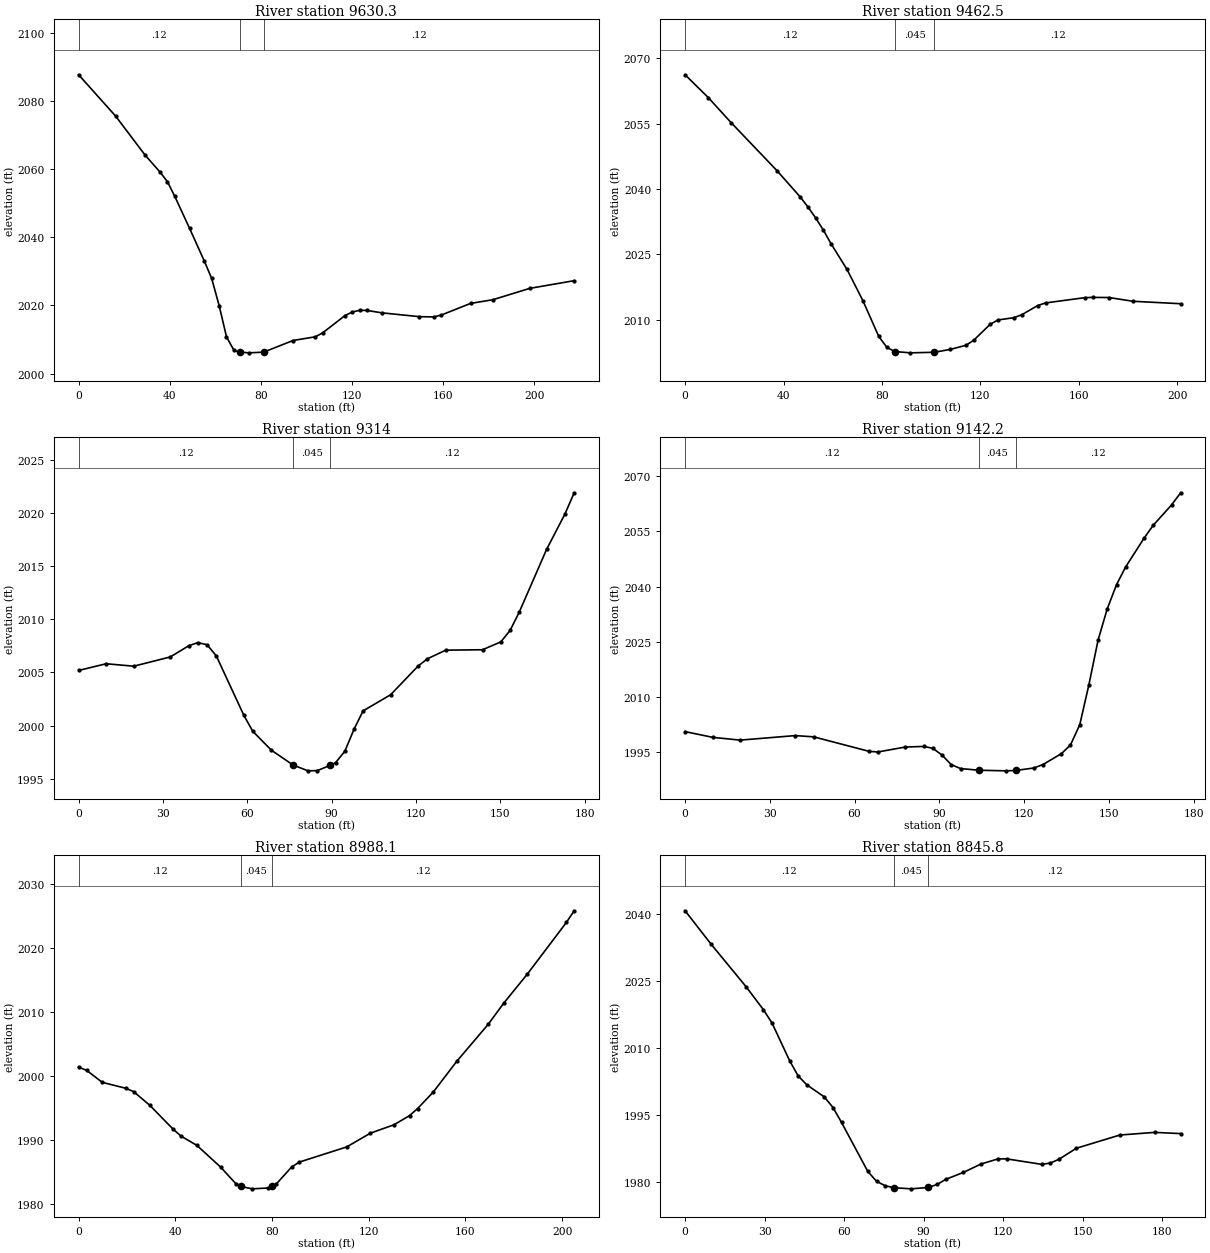
Type RM Length L Ch R = 1 ,9630.3  ,170.8,167.8,164.9
XS GIS Cut Line= 2
      1970754.16      235248.996     1970551.924      235168.991
#Sta/Elev= 30
       0 2087.71    16.2 2075.61    29.2 2064.11    35.7 2059.18      39  2056.3
    42.2 2052.03    48.7 2042.63    55.2 2032.99    58.4 2027.92    61.7  2019.9
    64.9 2010.79    68.2 2006.81   70.62 2006.33    74.7  2006.1    81.2  2006.3
    94.1 2009.72   103.9 2010.81   107.1 2011.95   116.9 2017.04   120.1 2018.08
   123.4  2018.6   126.6 2018.54   133.1 2017.84   149.3 2016.73   155.8 2016.63
   159.1 2017.17     172  2020.6   181.8 2021.69     198 2025.02   217.5 2027.28
#Mann= 3 ,-1 , 0
       0     .12       0   70.62    .045       0    81.2     .12       0
Bank Sta=70.62,81.2
XS Rating Curve= 0 ,0
Exp/Cntr=0.3,0.1

Type RM Length L Ch R = 1 ,9462.5  ,150.5,148.6,146.1
XS GIS Cut Line= 3
     1970811.942      235118.987     1970775.273      235072.317
     1970637.486       235037.87
#Sta/Elev= 30
       0 2066.25     9.4 2061.03    18.7 2055.26    37.5 2044.14    46.9 2038.12
      50 2035.84    53.1 2033.35    56.2 2030.57    59.4 2027.37    65.8 2021.56
    72.3 2014.34    78.7 2006.17      82 2003.66    85.2  2002.7    91.6  2002.4
   101.3 2002.53   107.8 2003.19   114.2 2004.14   117.4 2005.34   123.9 2008.91
   127.1 2009.94   133.6 2010.47   136.8 2011.13   143.3 2013.26   146.5 2013.86
   162.6 2015.08   165.9 2015.13   172.3  2015.1     182 2014.24   201.4 2013.68
#Mann= 3 ,-1 , 0
       0     .12       0    85.2    .045       0   101.3     .12       0
Bank Sta=85.2,101.3
XS Rating Curve= 0 ,0
Exp/Cntr=0.3,0.1

Type RM Length L Ch R = 1 ,9314    ,149,171.8,193.7
XS GIS Cut Line= 2
     1970846.389      234928.974     1970671.933      234903.417
#Sta/Elev= 30
       0 2005.19     9.8 2005.82    19.6 2005.59    32.6 2006.46    39.2 2007.52
    42.4 2007.81    45.7 2007.61      49 2006.55    58.8 2000.95      62 1999.44
    68.6 1997.67   76.28 1996.28    81.6 1995.73    84.9 1995.75    89.5 1996.25
    91.4  1996.5    94.7 1997.57      98 1999.66   101.2 2001.38     111  2002.9
   120.8 2005.61   124.1 2006.29   130.6  2007.1   143.7 2007.14   150.2 2007.88
   153.5 2008.96   156.7 2010.65   166.5  2016.6     173 2019.92   176.3 2021.93
#Mann= 3 ,-1 , 0
       0     .12       0   76.28    .045       0    89.5     .12       0
Bank Sta=76.28,89.5
XS Rating Curve= 0 ,0
Exp/Cntr=0.3,0.1

Type RM Length L Ch R = 1 ,9142.2  ,134.7,154.1,171.1
XS GIS Cut Line= 2
     1970849.722      234854.525     1970770.828      234697.847
#Sta/Elev= 30
       0 2000.59     9.8 1999.03    19.5 1998.28      39 1999.51    45.5 1999.17
      65 1995.25    68.2 1995.05      78 1996.41    84.5 1996.56    87.7 1996.05
      91 1994.17    94.2 1991.61    97.5 1990.55     104 1990.09   113.7 1989.93
     117 1990.03   123.4  1990.7   126.7 1991.65   133.2  1994.6   136.4 1996.94
   139.7 2002.47   142.9 2013.24   146.2 2025.53   149.4  2033.9   152.7 2040.52
   155.9  2045.3   162.4  2053.1   165.7 2056.67   172.2 2062.21   175.4  2065.5
#Mann= 3 ,-1 , 0
       0     .12       0     104    .045       0     117     .12       0
Bank Sta=104,117
XS Rating Curve= 0 ,0
Exp/Cntr=0.3,0.1

Type RM Length L Ch R = 1 ,8988.1  ,160.8,142.2,123
XS GIS Cut Line= 3
     1970908.615      234872.304      1970950.84      234752.295
     1970904.171      234690.069
#Sta/Elev= 30
       0 2001.32     3.3 2000.82     9.8 1998.94    19.6 1998.01    22.8 1997.48
    29.4 1995.37    39.1 1991.62    42.4 1990.53    48.9  1989.1    58.7 1985.71
    65.2 1983.04   67.05 1982.68    71.8  1982.3    78.3 1982.43   79.85 1982.69
    81.6 1982.98    88.1 1985.71    91.3 1986.48   110.9 1988.85   120.7    1991
   130.5 1992.32   136.9 1993.75   140.2 1994.84   146.7 1997.42   156.4 2002.22
   169.4    2008   175.8 2011.29   185.6 2015.85   201.8 2023.95     205 2025.76
#Mann= 3 ,-1 , 0
       0     .12       0   67.05    .045       0   79.85     .12       0
Bank Sta=67.05,79.85
XS Rating Curve= 0 ,0
Exp/Cntr=0.3,0.1

Type RM Length L Ch R = 1 ,8845.8  ,174.2,162.6,150.5
XS GIS Cut Line= 2
      1971109.74      234855.636     1971020.845       234691.18
#Sta/Elev= 30
       0 2040.83     9.8 2033.33      23 2023.78    29.5 2018.64    32.8  2015.6
    39.4 2007.19    42.6 2003.78    45.9 2001.74    52.5 1999.03    55.8 1996.63
      59 1993.29    68.9  1982.3    72.2 1980.08    75.4 1979.09    78.7 1978.63
    85.3 1978.38    91.8 1978.69    95.1 1979.38    98.4 1980.53     105 1982.08
   111.5 1983.93   118.1 1985.12   121.4  1985.1   134.5 1983.88   137.8 1984.18
     141 1985.02   147.6  1987.5     164 1990.47   177.1 1991.06   186.9 1990.79
#Mann= 3 ,-1 , 0
       0     .12       0    78.7    .045       0    91.8     .12       0
Bank Sta=78.7,91.8
XS Rating Curve= 0 ,0
Exp/Cntr=0.3,0.1

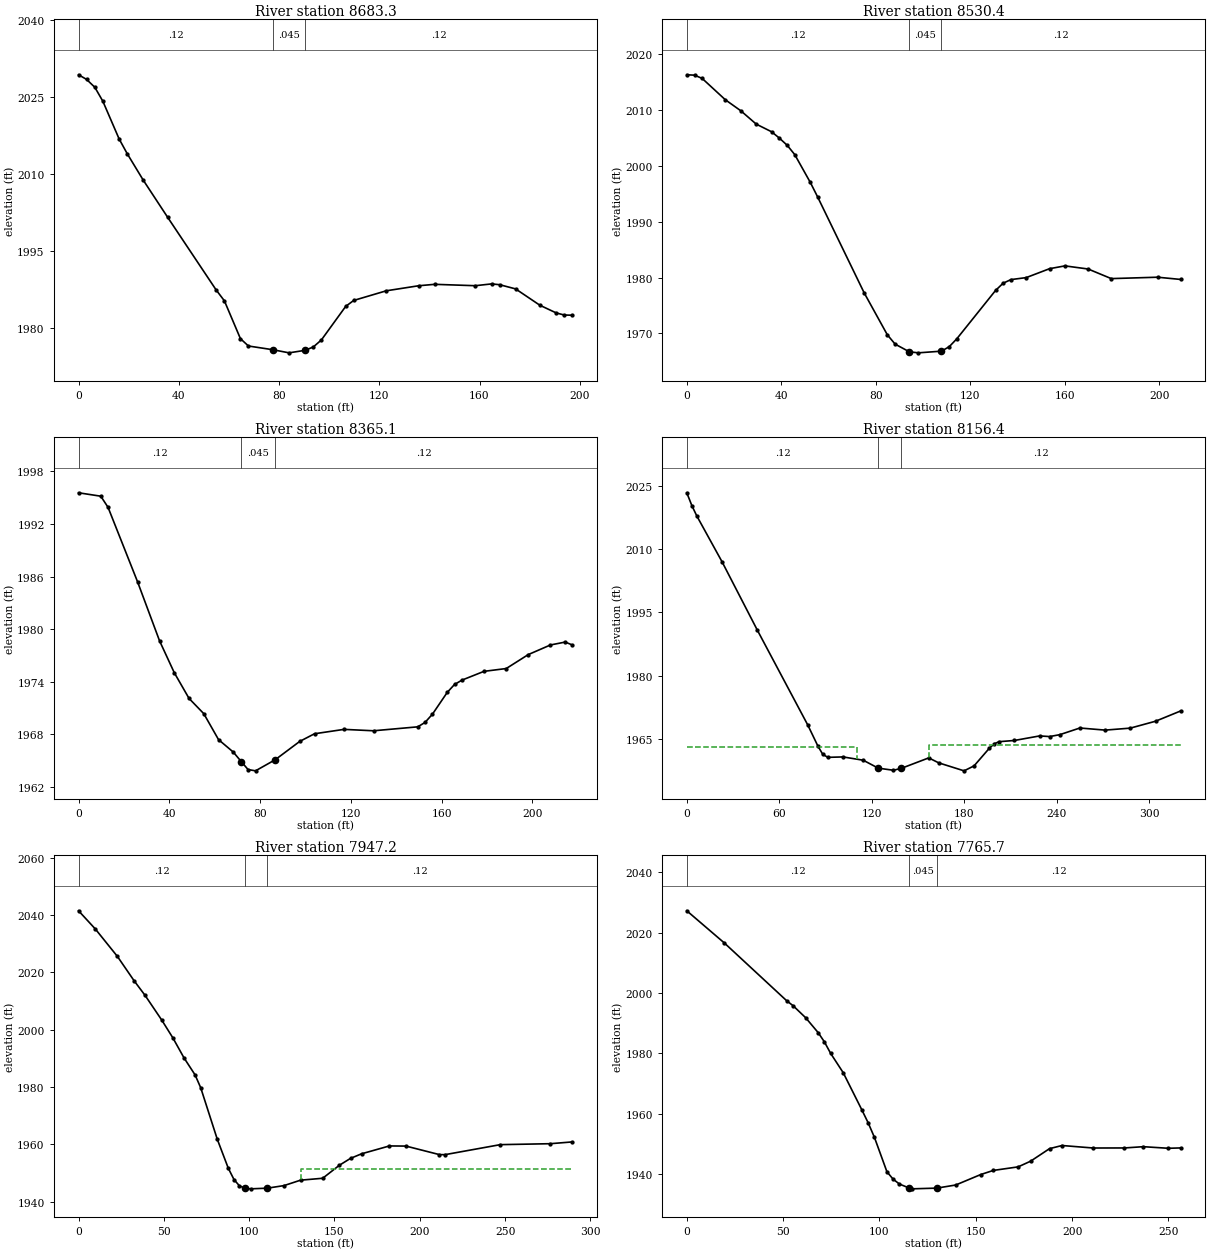
Type RM Length L Ch R = 1 ,8683.3  ,153.3,152.8,152
XS GIS Cut Line= 2
     1971267.529       234728.96      1971099.74       234625.62
#Sta/Elev= 30
       0 2029.31     3.2 2028.41     6.5 2026.87     9.7 2024.15    16.2  2016.8
    19.4 2013.95    25.8 2008.79    35.5 2001.58    54.9 1987.39    58.2 1985.26
    64.6 1977.89    67.8 1976.46    77.5 1975.74      84 1975.13    90.4 1975.62
    93.7 1976.28    96.9 1977.64   106.6 1984.18   109.8 1985.34   122.8 1987.22
   135.7  1988.2   142.1 1988.48   158.3 1988.21   164.8 1988.56     168 1988.41
   174.4 1987.59   184.1  1984.4   190.6 1982.91   193.8  1982.5   197.1 1982.46
#Mann= 3 ,-1 , 0
       0     .12       0    77.5    .045       0    90.4     .12       0
Bank Sta=77.5,90.4
XS Rating Curve= 0 ,0
Exp/Cntr=0.3,0.1

Type RM Length L Ch R = 1 ,8530.4  ,167,165.3,163.4
XS GIS Cut Line= 2
     1971355.313      234601.174     1971174.189      234496.722
#Sta/Elev= 30
       0 2016.35     3.3 2016.28     6.5  2015.7    16.3 2011.88    22.9 2009.89
    29.4 2007.51    35.9 2006.14    39.2    2005    42.5 2003.72    45.7 2002.05
    52.3 1997.06    55.5 1994.37    75.1 1977.27    84.9 1969.76    88.2 1968.09
    94.2 1966.72      98 1966.53   107.8 1966.83   111.1 1967.63   114.3 1969.04
   130.7  1977.7   133.9    1979   137.2 1979.65   143.7 1980.01   153.6 1981.61
   160.1 1982.11   169.9 1981.55   179.7 1979.83   199.3 1980.08   209.1 1979.68
#Mann= 3 ,-1 , 0
       0     .12       0    94.2    .045       0   107.8     .12       0
Bank Sta=94.2,107.8
XS Rating Curve= 0 ,0
Exp/Cntr=0.3,0.1

Type RM Length L Ch R = 1 ,8365.1  ,209.7,208.7,207.6
XS GIS Cut Line= 2
     1971433.096      234450.053     1971236.416      234356.713
#Sta/Elev= 30
       0 1995.57     9.8 1995.18      13 1993.91      26 1985.42    35.7 1978.68
    42.2 1975.04    48.7 1972.11    55.2 1970.37    61.7 1967.41    68.2 1965.99
    71.7 1964.91    74.7    1964      78 1963.85    86.7 1965.12    97.5 1967.21
     104 1968.08     117 1968.58     130 1968.42   149.5 1968.87   152.7 1969.37
     156 1970.32   162.5  1972.8   165.7  1973.7     169  1974.2   178.7  1975.2
   188.5 1975.52   198.2 1977.11     208 1978.21   214.5 1978.54   217.7  1978.2
#Mann= 3 ,-1 , 0
       0     .12       0    71.7    .045       0    86.7     .12       0
Bank Sta=71.7,86.7
XS Rating Curve= 0 ,0
Exp/Cntr=0.3,0.1

Type RM Length L Ch R = 1 ,8156.4  ,218.2,209.2,199.5
XS GIS Cut Line= 2
     1971572.381      234278.152     1971276.724      234154.961
#Sta/Elev= 30
       0 2023.34     3.3 2020.29     6.5 2017.84    22.9 2006.95    45.8 1990.72
    78.4  1968.3      85 1963.28    88.2 1961.29    91.5 1960.59   101.3 1960.69
   114.4 1959.91   124.2 1958.02     134 1957.53  139.11 1957.98   156.9 1960.46
   163.4 1959.28   179.8 1957.39   186.3 1958.57   196.1 1962.71   199.4 1963.82
   202.6 1964.31   212.4 1964.59   228.8 1965.67   235.3 1965.52   241.9 1965.97
   254.9 1967.55   271.3 1967.05   287.6 1967.52     304 1969.16   320.3  1971.6
#Mann= 3 ,-1 , 0
       0     .12       0   124.2    .045       0  139.11     .12       0
#XS Ineff= 2 , 0
          110.53 1963.11  157.12         1963.51
Permanent Ineff=
       F       F
Bank Sta=124.2,139.11
XS Rating Curve= 0 ,0
Exp/Cntr=0.3,0.1

Type RM Length L Ch R = 1 ,7947.2  ,177.9,181.5,184.2
XS GIS Cut Line= 2
     1971631.923      234033.824     1971342.425       234037.93
#Sta/Elev= 30
       0 2041.52     9.8 2035.19    22.8 2025.57    32.5 2017.15      39 2011.99
    48.8 2003.35    55.3 1997.15    61.8  1990.2    68.3 1984.25    71.6 1979.77
    81.3 1961.81    87.8 1951.63    91.1 1947.74    94.3 1945.53    97.6 1944.72
   100.8 1944.49   110.6 1944.72   120.4 1945.62   130.1 1947.51   143.1 1948.18
   152.9 1952.73   159.4 1955.12   165.9 1956.72   182.2 1959.46   191.9 1959.41
   211.4 1956.45   214.7 1956.41   247.2 1959.91   276.5 1960.24   289.5 1960.87
#Mann= 3 ,-1 , 0
       0     .12       0    97.6    .045       0   110.6     .12       0
#XS Ineff= 2 , 0
                          130.65         1951.35
Permanent Ineff=
       F       F
Bank Sta=97.6,110.6
XS Rating Curve= 0 ,0
Exp/Cntr=0.3,0.1

Type RM Length L Ch R = 1 ,7765.7  ,208.9,217.4,224.7
XS GIS Cut Line= 2
     1971658.614      233875.729      1971404.02      233844.932
#Sta/Elev= 30
       0 2027.23    19.5 2016.56    51.9 1997.39    55.2 1995.76    61.7 1991.79
    68.2 1986.85    71.4 1983.82    74.7 1979.95    81.2 1973.57    90.9 1961.22
    94.1 1957.03    97.4 1952.15   103.9 1940.73   107.1 1938.29   110.4 1936.66
  115.49 1935.34   116.9 1935.08   129.8 1935.32   139.6 1936.35   152.6 1939.82
   159.1 1941.18     172 1942.36   178.5 1944.25   188.3  1948.4   194.8 1949.44
     211 1948.61   227.2 1948.63     237 1949.05     250 1948.52   256.4 1948.64
#Mann= 3 ,-1 , 0
       0     .12       0  115.49    .045       0   129.8     .12       0
Bank Sta=115.49,129.8
XS Rating Curve= 0 ,0
Exp/Cntr=0.3,0.1

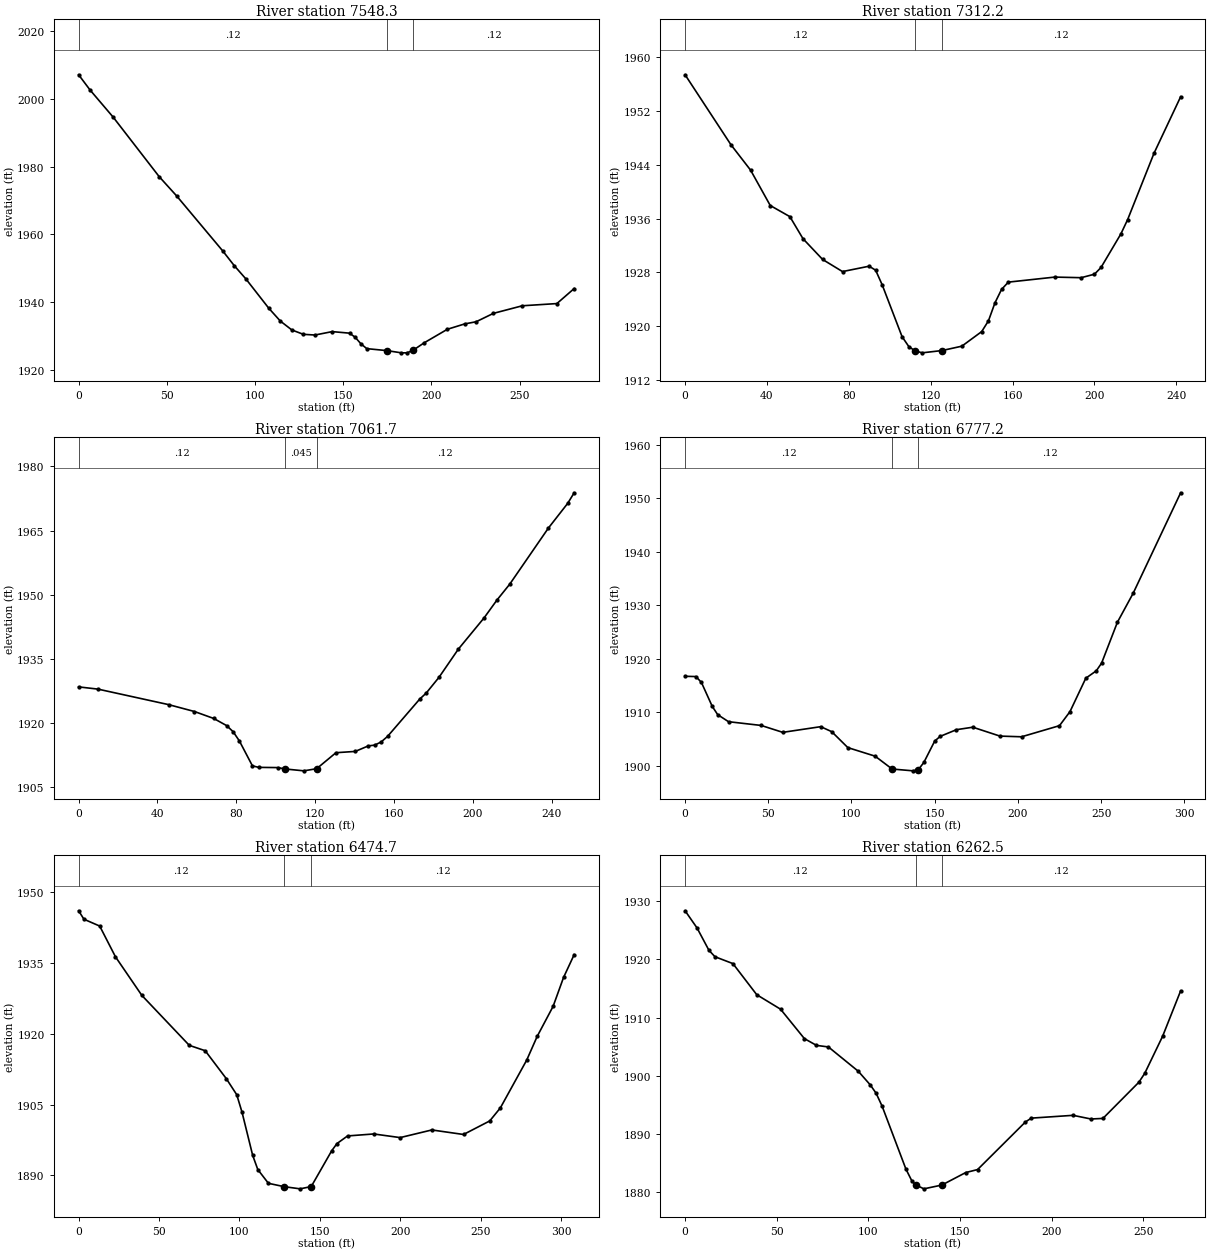
Type RM Length L Ch R = 1 ,7548.3  ,235.4,236.1,235.4
XS GIS Cut Line= 2
     1971664.774      233750.486     1971412.233      233627.295
#Sta/Elev= 30
       0  2007.1     6.5 2002.59    19.6 1994.58    45.7    1977    55.5 1971.37
    81.7 1955.09    88.2 1950.76    94.8 1946.84   107.8 1938.17   114.4 1934.35
   120.9 1931.74   127.4 1930.45     134 1930.24   143.8 1931.25   153.6 1930.79
   156.8 1929.59   160.1 1927.63   163.4 1926.22  174.94 1925.63     183 1924.98
   186.2 1924.98   189.5 1925.69     196 1927.96   209.1 1931.94   218.9 1933.52
   225.4 1934.16   235.2 1936.64   251.6 1938.88   271.2 1939.53     281 1943.97
#Mann= 3 ,-1 , 0
       0     .12       0  174.94    .045       0   189.5     .12       0
Bank Sta=174.94,189.5
XS Rating Curve= 0 ,0
Exp/Cntr=0.3,0.1

Type RM Length L Ch R = 1 ,7312.2  ,256.2,250.5,242.5
XS GIS Cut Line= 3
      1971714.05      233543.115     1971670.933      233495.892
     1971510.785      233417.871
#Sta/Elev= 30
       0 1957.41    22.4    1947      32 1943.22    41.6 1937.96    51.2  1936.3
    57.6 1933.02    67.2 1929.93    76.9 1928.13    89.9 1928.93    93.1 1928.33
    96.3 1926.15     106 1918.45   109.3 1916.97   112.2 1916.36   115.8 1916.04
   125.5 1916.38   135.2 1917.03   144.9  1919.2   148.2  1920.8   151.4 1923.49
   154.6 1925.47   157.9 1926.56   180.6 1927.31   193.5 1927.22     200 1927.74
   203.2 1928.74   212.9 1933.73   216.2 1935.86   229.1 1945.74   242.1 1954.14
#Mann= 3 ,-1 , 0
       0     .12       0   112.2    .045       0   125.5     .12       0
Bank Sta=112.2,125.5
XS Rating Curve= 0 ,0
Exp/Cntr=0.3,0.1

Type RM Length L Ch R = 1 ,7061.7  ,287.4,284.5,281.2
XS GIS Cut Line= 2
     1971818.762       233261.83     1971570.328       233222.82
#Sta/Elev= 30
       0 1928.45     9.8 1927.93    45.7  1924.3    58.8 1922.69    68.6 1921.06
    75.1  1919.4    78.4 1917.98    81.6  1915.8    88.2 1909.99    91.4 1909.63
   101.2 1909.58   104.5 1909.27   114.3 1908.82   120.8 1909.32   130.6 1913.06
   140.4 1913.36     147 1914.65   150.2 1914.83   153.5 1915.56   156.8 1916.88
   173.1 1925.59   176.4    1927   182.9 1930.69   192.7 1937.27   205.8  1944.6
   212.3 1948.75   218.8 1952.47   238.4 1965.58   248.2 1971.36   251.5 1973.84
#Mann= 3 ,-1 , 0
       0     .12       0   104.5    .045       0   120.8     .12       0
Bank Sta=104.5,120.8
XS Rating Curve= 0 ,0
Exp/Cntr=0.3,0.1

Type RM Length L Ch R = 1 ,6777.2  ,310.5,302.5,292.4
XS GIS Cut Line= 3
     1971845.453       232964.12      1971623.71      232960.014
     1971551.849      232984.652
#Sta/Elev= 30
       0 1916.74     6.5 1916.69     9.8  1915.6    16.3 1911.13    19.6 1909.57
    26.1 1908.26    45.7 1907.56    58.7 1906.27    81.5 1907.33    88.1  1906.4
    97.8 1903.42   114.2 1901.82   124.4 1899.42     137 1899.08   140.2 1899.31
   143.5 1900.66     150 1904.64   153.3 1905.52   163.1 1906.77   172.9 1907.23
   189.2 1905.57   202.2 1905.44     225 1907.52   231.3 1910.14   240.8 1916.38
   247.1 1917.76   250.3  1919.2   259.8 1926.84   269.3 1932.27   297.8 1951.02
#Mann= 3 ,-1 , 0
       0     .12       0   124.4    .045       0   140.2     .12       0
Bank Sta=124.4,140.2
XS Rating Curve= 0 ,0
Exp/Cntr=0.3,0.1

Type RM Length L Ch R = 1 ,6474.7  ,211.9,212.2,212.3
XS GIS Cut Line= 2
     1971771.539      232670.516     1971484.094      232781.387
#Sta/Elev= 30
       0 1946.08     3.3 1944.29    13.1 1942.84    22.9 1936.33    39.3 1928.15
    68.8 1917.56    78.7 1916.42    91.8 1910.51    98.3  1907.1   101.6 1903.38
   108.2 1894.26   111.4 1891.24     118 1888.32   127.8 1887.61   137.7 1887.15
  144.61 1887.63   157.3 1895.19   160.6 1896.74   167.2 1898.36   183.5 1898.78
   199.9 1898.01   219.6 1899.63   239.3 1898.67   255.6 1901.54   262.2  1904.3
   278.6 1914.44   285.1 1919.46     295 1925.82   301.5 1931.95   308.1 1936.79
#Mann= 3 ,-1 , 0
       0     .12       0   127.8    .045       0  144.61     .12       0
Bank Sta=127.8,144.61
XS Rating Curve= 0 ,0
Exp/Cntr=0.3,0.1

Type RM Length L Ch R = 1 ,6262.5  ,215.7,230,244.4
XS GIS Cut Line= 2
     1971672.986      232483.677     1971420.446      232580.176
#Sta/Elev= 30
       0 1928.34     6.5  1925.4      13 1921.56    16.3 1920.45    26.1 1919.27
    39.1 1913.93    52.1 1911.44    65.1 1906.39    71.7 1905.23    78.2 1904.96
    94.5 1900.79     101 1898.46   104.2 1897.03   107.5  1894.8   120.5 1883.99
   123.8 1881.92  125.81 1881.29   130.3  1880.6   140.1 1881.25   153.1 1883.39
   159.6 1883.91   185.7 1892.08   188.9 1892.74   211.7 1893.22   221.5 1892.59
     228 1892.69   247.6  1898.9   250.8 1900.42   260.6 1906.82   270.4 1914.59
#Mann= 3 ,-1 , 0
       0     .12       0  125.81    .045       0   140.1     .12       0
Bank Sta=125.81,140.1
XS Rating Curve= 0 ,0
Exp/Cntr=0.3,0.1

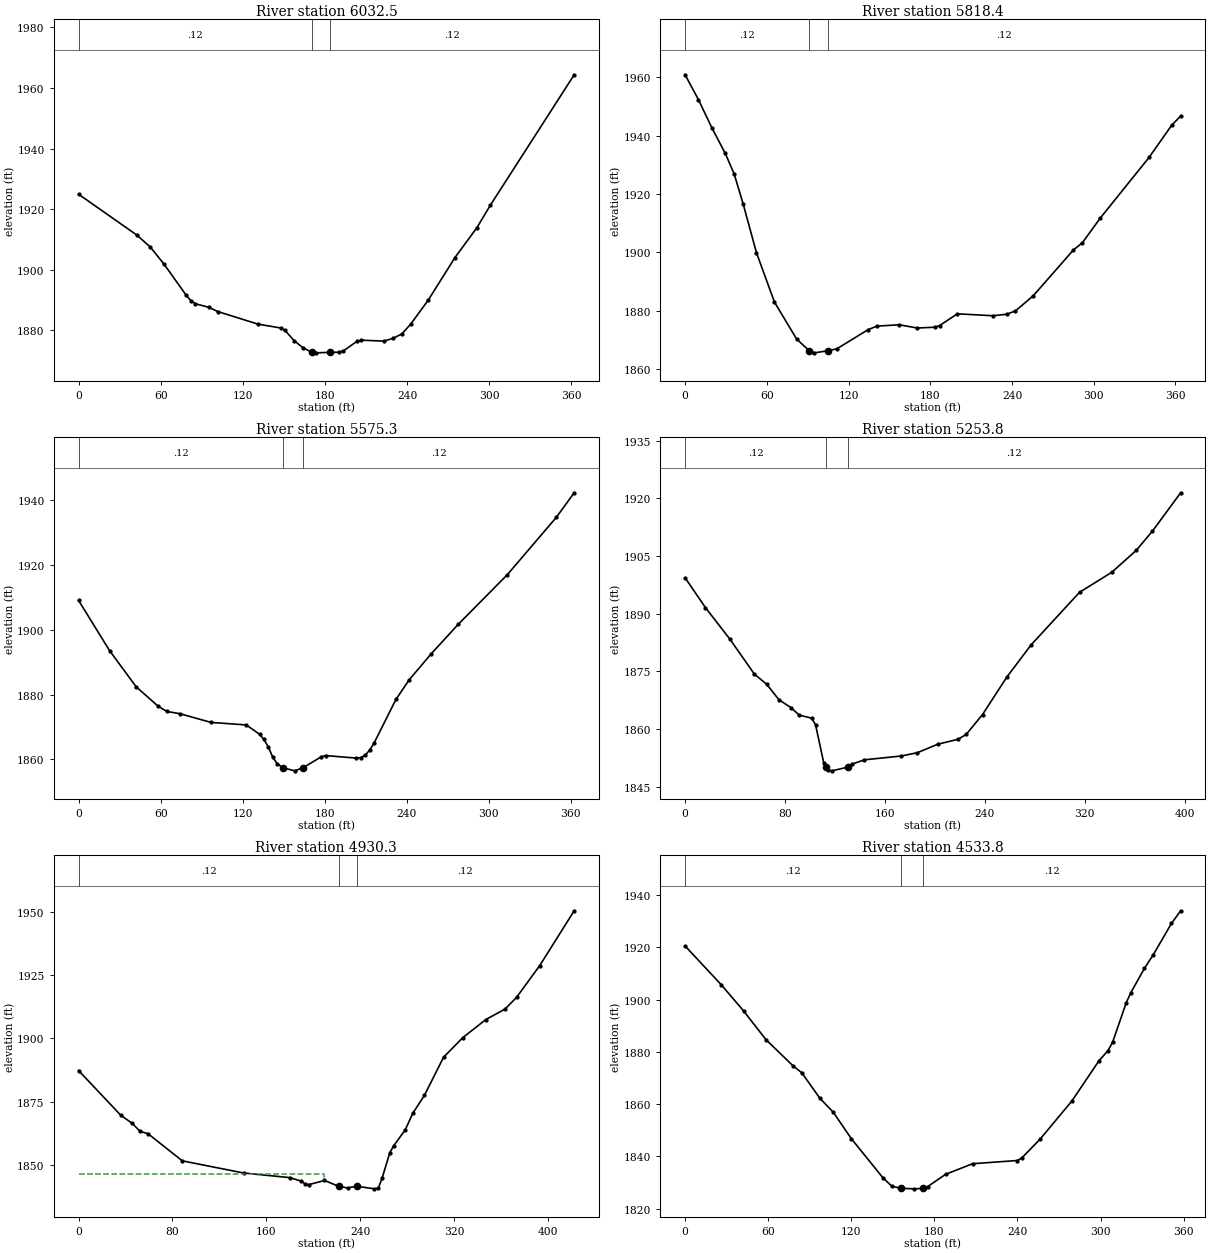
Type RM Length L Ch R = 1 ,6032.5  ,231.2,214.1,196.4
XS GIS Cut Line= 3
     1971648.348      232376.912     1971414.286      232313.264
     1971305.468       232362.54
#Sta/Elev= 30
       0 1924.93    42.6 1911.44    52.4  1907.5    62.3 1901.94    78.7 1891.55
      82 1889.84    85.2 1888.83    95.1 1887.64   101.6 1886.25   131.1 1882.08
   147.5 1880.83   150.8    1880   157.3 1876.69   163.9  1874.3   170.4 1872.79
   173.7 1872.62   183.6  1872.8   190.1 1872.81   193.4 1873.26   203.2 1876.37
   206.5  1876.8   222.9 1876.49   229.4 1877.36     236 1878.82   242.6 1882.09
   255.5 1890.09   274.8 1903.98     291 1913.94   300.7 1921.27     362 1964.35
#Mann= 3 ,-1 , 0
       0     .12       0   170.4    .045       0   183.6     .12       0
Bank Sta=170.4,183.6
XS Rating Curve= 0 ,0
Exp/Cntr=0.3,0.1

Type RM Length L Ch R = 1 ,5818.4  ,258.8,243.1,226.2
XS GIS Cut Line= 2
     1971592.912      232085.361     1971272.617      232257.828
#Sta/Elev= 30
       0 1960.87     9.8 1952.34    19.7 1942.63    29.5 1933.91      36  1926.9
    42.6 1916.61    52.4 1899.86    65.6 1882.94    81.9 1870.24   91.17 1866.23
      95 1865.53   104.9 1866.25   111.4  1866.9   134.4  1873.5   140.9  1874.7
   157.3 1875.15   170.4 1874.04   183.5 1874.32   186.8 1874.87   199.9 1878.91
   226.1 1878.25     236 1878.76   242.5 1879.89   255.6  1885.1   285.1 1900.82
   291.7  1903.3   304.8 1911.74   340.8 1932.64   357.2 1943.55   363.8 1946.72
#Mann= 3 ,-1 , 0
       0     .12       0   91.17    .045       0   104.9     .12       0
Bank Sta=91.17,104.9
XS Rating Curve= 0 ,0
Exp/Cntr=0.3,0.1

Type RM Length L Ch R = 1 ,5575.3  ,302.6,321.4,339.4
XS GIS Cut Line= 4
     1971414.286       231884.15     1971332.159      231935.479
     1971278.777      232077.148     1971188.437      232146.956
#Sta/Elev= 30
       0 1909.04    22.6 1893.57      42 1882.42    58.1 1876.39    64.6 1874.76
    74.2 1874.06    96.8 1871.38   122.6  1870.6   132.3 1867.73   135.5 1866.14
   138.7 1863.83   141.9 1860.71   145.2 1858.62   149.2 1857.39     158 1856.42
   164.2 1857.39   177.4 1860.75   180.6 1861.14   203.2 1860.35   206.4  1860.5
   209.6 1861.28   212.8 1862.78     216 1864.95   232.1 1878.51   241.8 1884.57
     258 1892.64   277.6 1901.67   313.5    1917   349.4 1934.75   362.4 1942.31
#Mann= 3 ,-1 , 0
       0     .12       0   149.2    .045       0   164.2     .12       0
Bank Sta=149.2,164.2
XS Rating Curve= 0 ,0
Exp/Cntr=0.3,0.1

Type RM Length L Ch R = 1 ,5253.8  ,316.3,323.5,329.7
XS GIS Cut Line= 3
     1971295.202      231719.896     1971089.885      231804.076
     1971050.874       231974.49
#Sta/Elev= 30
       0 1899.33    16.3 1891.58    35.9 1883.37    55.5 1874.29    65.3 1871.68
    75.1 1867.65    84.8 1865.58    91.4 1863.65   101.2 1862.87   104.4  1861.2
     111 1851.23  112.93 1850.14   114.2 1849.42   117.5 1849.17   130.5 1850.15
   133.8 1850.94   143.6 1852.04     173 1853.02     186 1853.89   202.3 1856.09
   218.6 1857.38   225.1 1858.65   238.1  1863.8   257.5  1873.5   276.9 1881.87
   315.8 1895.57   341.7 1900.79   361.1 1906.44   374.1 1911.44   396.7 1921.42
#Mann= 3 ,-1 , 0
       0     .12       0  112.93    .045       0   130.5     .12       0
Bank Sta=112.93,130.5
XS Rating Curve= 0 ,0
Exp/Cntr=0.3,0.1

Type RM Length L Ch R = 1 ,4930.3  ,386.4,396.5,401.8
XS GIS Cut Line= 2
     1971165.852      231537.164     1970747.005      231592.599
#Sta/Elev= 30
       0 1887.26      36 1869.57    45.8 1866.36    52.4 1863.19      59 1862.35
    88.4 1851.57   140.8 1846.75   180.1 1844.94     190  1843.5   193.2 1842.38
   196.5 1842.19   209.6 1843.81     222 1841.45   229.3 1840.87     237 1841.53
   252.2  1840.5   255.5 1840.73   258.7 1844.66   265.3 1854.75   268.6 1857.54
   278.4 1863.77   284.9 1870.35   294.8 1877.45   311.1 1892.51   327.5 1900.28
   347.2 1907.45   363.6  1911.6   373.4 1916.24     393  1928.7   422.5 1950.46
#Mann= 3 ,-1 , 0
       0     .12       0     222    .045       0     237     .12       0
#XS Ineff= 2 , 0
          208.98 1846.28
Permanent Ineff=
       F       F
Bank Sta=222,237
XS Rating Curve= 0 ,0
Exp/Cntr=0.3,0.1

Type RM Length L Ch R = 1 ,4533.8  ,233,231.2,229.5
XS GIS Cut Line= 3
     1971216.365      231229.491     1970963.486      231187.996
     1970861.982      231186.071
#Sta/Elev= 30
       0 1920.53      26 1905.75    42.2 1895.69    58.4 1884.66    77.8 1874.71
    84.3 1871.95    97.3 1862.23     107 1856.88     120 1846.77   142.7 1831.86
   149.2 1828.56   155.7 1827.77   165.4 1827.54   171.9 1827.71   175.2 1828.42
   188.1  1833.1   207.6 1837.16     240 1838.39   243.3 1839.46   256.3 1846.55
   279.2 1861.13   298.8 1876.55   305.4  1880.5   308.7 1883.72   318.5 1898.77
   321.8 1902.61   331.6 1911.92   338.1 1917.23   351.2 1929.18   357.8 1934.01
#Mann= 3 ,-1 , 0
       0     .12       0   155.7    .045       0   171.9     .12       0
Bank Sta=155.7,171.9
XS Rating Curve= 0 ,0
Exp/Cntr=0.3,0.1

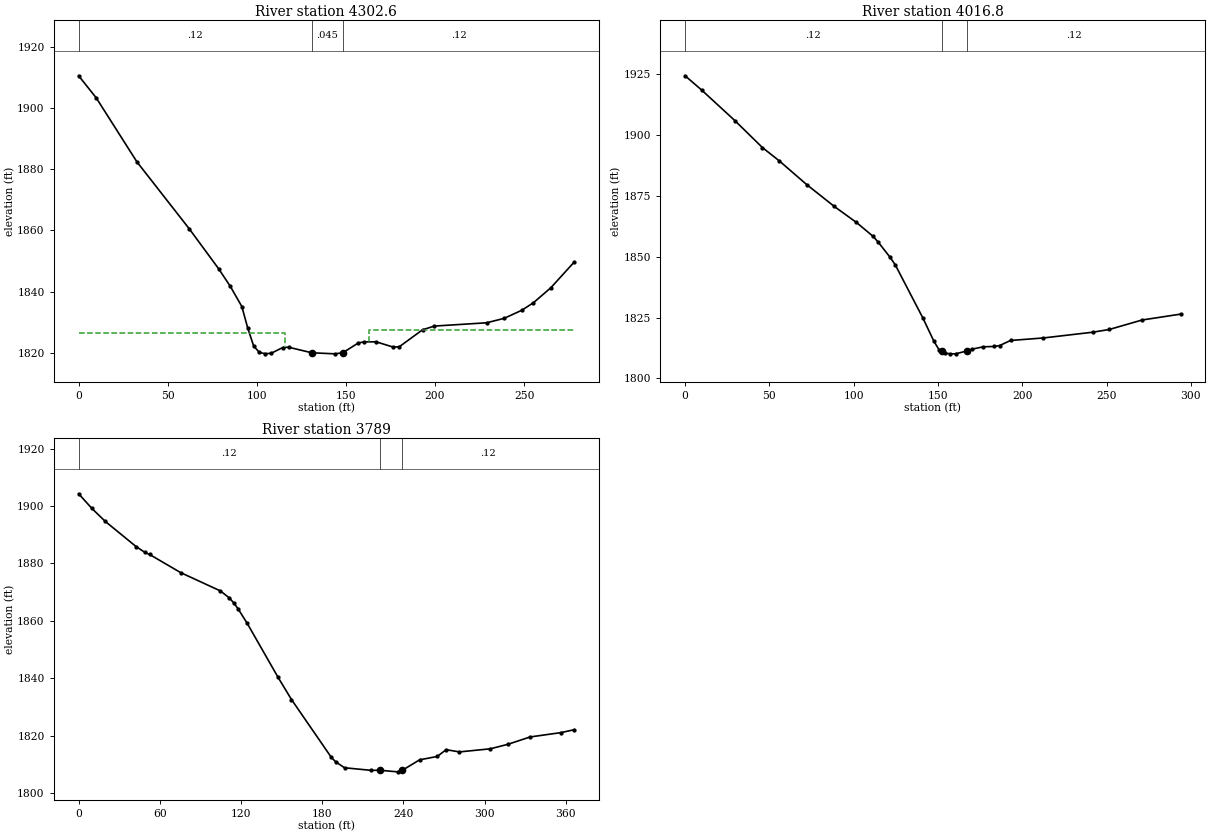
Type RM Length L Ch R = 1 ,4302.6  ,293.2,285.8,278
XS GIS Cut Line= 2
     1971204.862       230984.86     1970927.684      230962.275
#Sta/Elev= 30
       0  1910.6     9.8 1903.44    32.7 1882.45    62.2 1860.45    78.5 1847.53
    85.1 1841.74    91.6 1835.11    94.9 1828.08    98.2 1822.25   101.4  1820.1
   104.7 1819.69     108 1819.81   114.5 1821.69   117.8 1821.81   130.9 1819.98
     144 1819.64  148.33 1820.02     157 1823.22   160.3 1823.55   166.9 1823.58
   176.7 1821.82     180 1821.98     193  1827.5   199.6 1828.72     229  1829.8
   238.8 1831.25   248.6 1833.87   255.2 1836.34     265 1841.26   278.1 1849.65
#Mann= 3 ,-1 , 0
       0     .12       0   130.9    .045       0  148.33     .12       0
#XS Ineff= 2 , 0
          115.79 1826.35  163.16         1827.36
Permanent Ineff=
       F       F
Bank Sta=130.9,148.33
XS Rating Curve= 0 ,0
Exp/Cntr=0.3,0.1

Type RM Length L Ch R = 1 ,4016.8  ,219.2,227.8,233.5
XS GIS Cut Line= 3
      1971196.65      230717.947     1971059.087      230687.149
     1970911.258       230726.16
#Sta/Elev= 30
       0 1924.43     9.8 1918.58    29.5 1906.02    45.9  1894.9    55.7 1889.54
    72.1 1879.72    88.5 1870.71   101.6 1864.15   111.5 1858.42   114.7  1855.9
   121.3 1850.06   124.6 1846.78     141  1824.9   147.5  1815.4   150.7 1811.69
  152.08 1811.16     154 1810.42   157.2 1810.13   160.5 1810.15     167 1811.29
   170.1 1812.04   176.8 1813.02   183.3 1813.16   186.5 1813.52     193 1815.62
   212.5 1816.66   241.8 1819.02   251.6 1820.15   271.1 1824.05   293.9 1826.46
#Mann= 3 ,-1 , 0
       0     .12       0  152.08    .045       0     167     .12       0
Bank Sta=152.08,167
XS Rating Curve= 0 ,0
Exp/Cntr=0.3,0.1

Type RM Length L Ch R = 1 ,3789    ,199.5,217.7,235.1
XS GIS Cut Line= 3
      1971196.65      230580.384     1971040.608      230483.885
     1970857.876      230481.832
#Sta/Elev= 30
       0  1904.3     9.8 1899.19    19.7 1894.66    42.6 1885.84    49.1 1883.83
    52.4 1883.15    75.4 1876.81   104.8 1870.42   111.4 1867.96   114.7 1866.22
   117.9 1864.13   124.5 1859.18   147.4 1840.28   157.3 1832.55   186.7 1812.41
     190 1810.82   196.5 1808.76   216.1 1807.86   222.6 1807.89   235.7 1807.34
     239 1807.83     252 1811.53     265  1812.7   271.6 1815.07   281.4 1814.29
   304.2 1815.37   317.3 1816.95   333.6  1819.5   356.4 1821.02   366.2 1822.02
#Mann= 3 ,-1 , 0
       0     .12       0   222.6    .045       0     239     .12       0
Bank Sta=222.6,239
XS Rating Curve= 0 ,0
Exp/Cntr=0.3,0.1