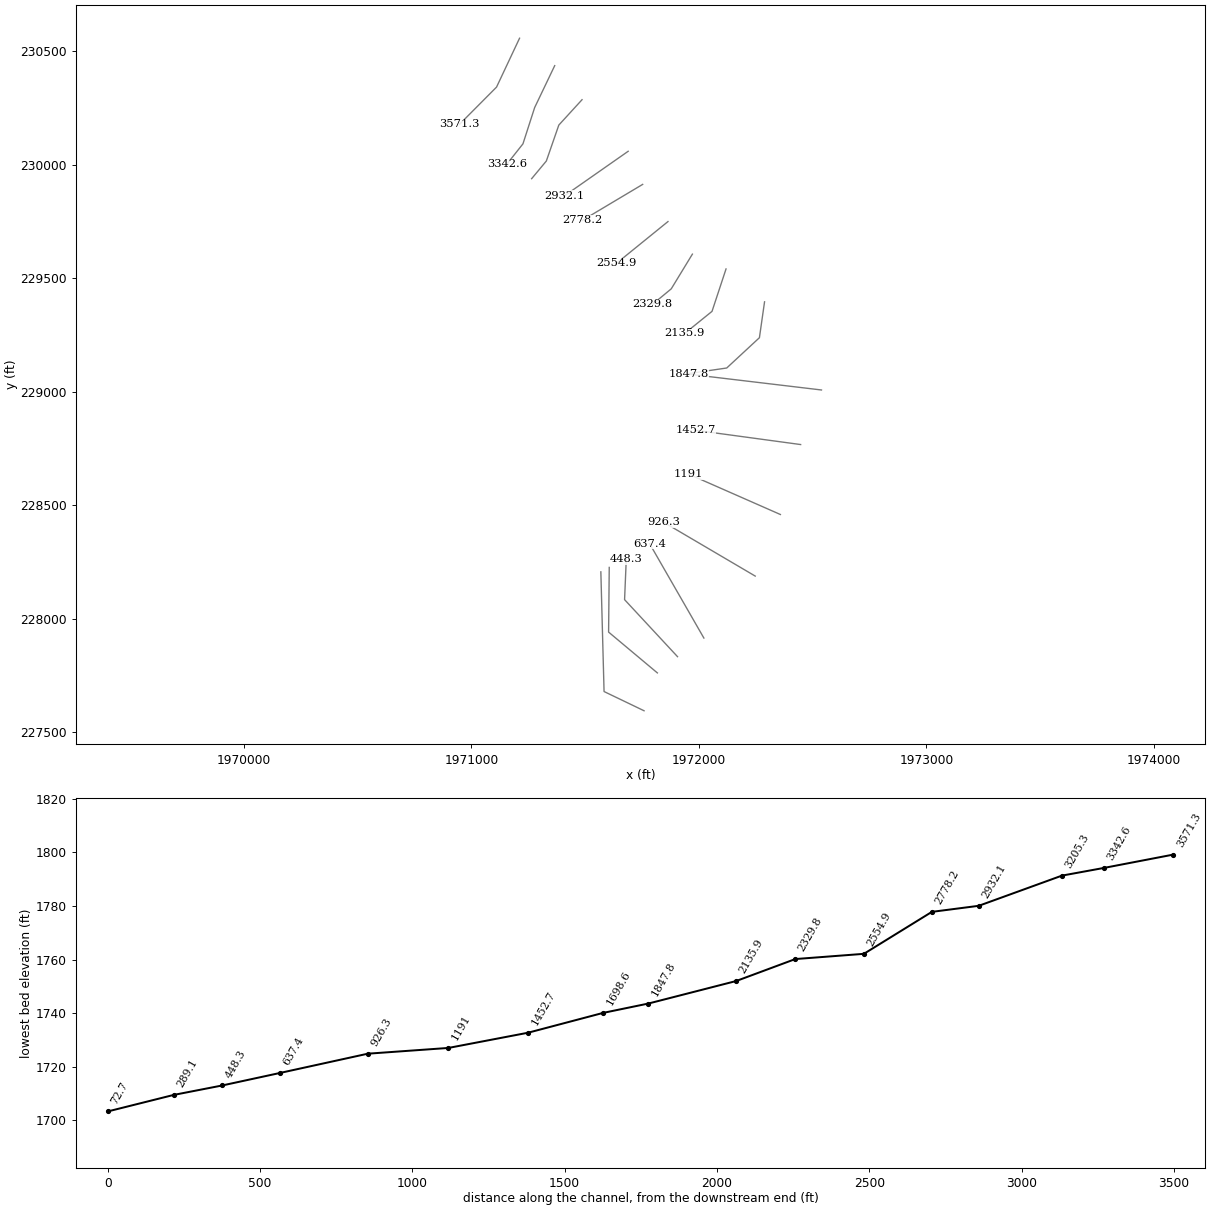
HEC-RAS study PRKRCK.prj: PRKRCK

--- PRKRCK.g01 (geometry) --- (continued)

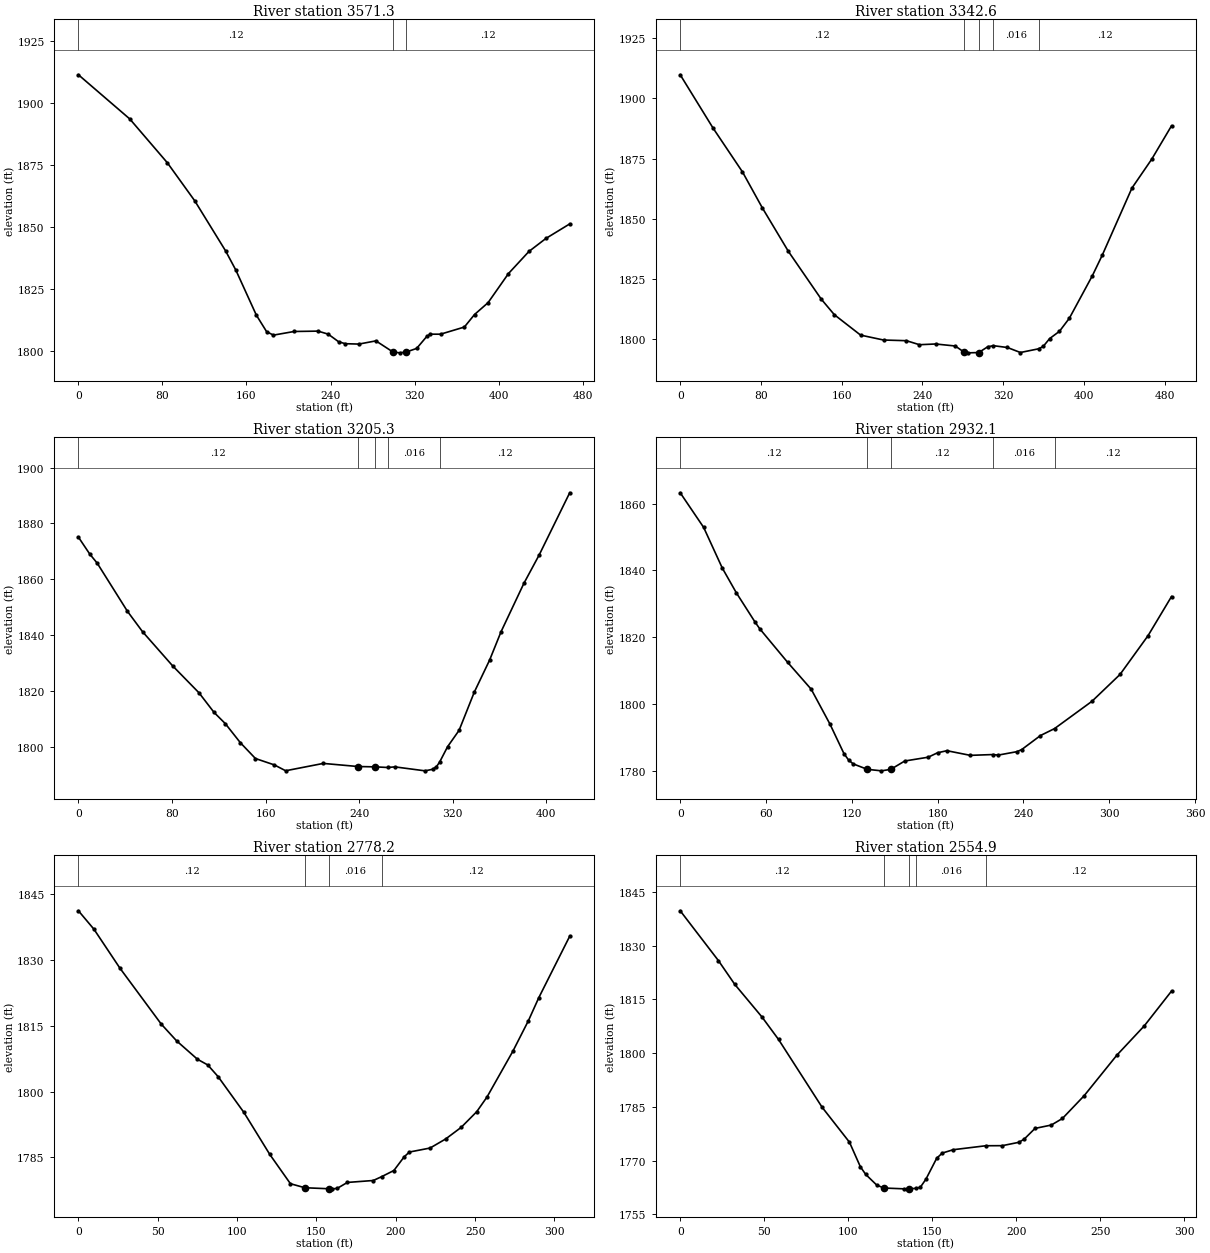
Type RM Length L Ch R = 1 ,3571.3  ,218,228.7,239.2
XS GIS Cut Line= 3
      1971211.88      230556.959     1971110.751      230341.681
     1970948.859      230178.487
#Sta/Elev= 30
       0 1911.24    48.9 1893.44    84.7 1875.77   110.8 1860.43   140.1  1840.3
   149.9 1832.52   169.4  1814.4   179.2 1807.72   185.7 1806.36   205.3 1807.82
   228.1 1807.97   237.8 1806.75   247.6 1803.72     254  1802.9     267 1802.75
   283.2 1804.04   299.4 1799.57   305.8 1799.22   312.2 1799.57     322    1801
   331.7 1805.86     335 1806.74   344.7 1806.73   367.4 1809.61   377.1 1814.66
     390 1819.44   409.4 1831.16   428.9 1840.07   445.1 1845.32   467.7 1851.16
#Mann= 3 ,-1 , 0
       0     .12       0   299.4    .045       0   312.2     .12       0
Bank Sta=299.4,312.2
XS Rating Curve= 0 ,0
Exp/Cntr=0.3,0.1

Type RM Length L Ch R = 1 ,3342.6  ,137.8,137.3,136.9
XS GIS Cut Line= 4
     1971366.411      230436.071     1971278.216      230251.348
     1971226.827      230091.626     1971155.994      230002.043
#Sta/Elev= 30
       0 1909.83    32.5 1887.69    61.7 1869.43    81.2 1854.61   107.2 1836.38
   139.7 1816.56   152.7 1810.07   178.7 1801.59   201.4 1799.55   224.1 1799.27
     237  1797.6   253.1  1797.9   272.5 1797.06   280.7 1794.65   285.4 1794.22
   295.7 1794.34   304.7 1796.76  310.28 1797.19   324.1 1796.44     337 1794.36
  354.99 1795.89   359.6 1796.89     366 1800.15   375.7 1803.17   385.5  1808.6
   408.4 1826.37   418.2 1834.92   447.5 1862.73   467.1 1874.73   486.7  1888.6
#Mann= 5 ,-1 , 0
       0     .12       0   280.7    .045       0   295.7     .12       0
  310.28    .016       0  354.99     .12       0
Bank Sta=280.7,295.7
XS Rating Curve= 0 ,0
Exp/Cntr=0.3,0.1

Type RM Length L Ch R = 1 ,3205.3  ,286.7,273.2,258.3
XS GIS Cut Line= 4
      1971486.55      230286.071     1971384.466      230174.265
     1971329.605      230015.932     1971265.022      229938.154
#Sta/Elev= 30
       0  1875.1     9.7 1869.04    16.1 1865.76    41.9 1848.54    54.8 1841.24
    80.5 1829.01   103.1 1819.32     116 1812.29   125.6 1808.28   138.5 1801.43
   151.4 1795.77   167.5 1793.49   177.2 1791.39   209.4 1794.02     239 1792.91
     254 1792.78  264.51 1792.56   270.6 1792.78   296.4 1791.36   302.8 1791.91
   306.1 1792.82  308.84 1794.48   315.7 1800.03   325.5 1805.87   338.5 1819.56
   351.6 1831.04   361.4 1841.22   380.9 1858.53     394 1868.73   420.1    1891
#Mann= 5 ,-1 , 0
       0     .12       0     239    .045       0     254     .12       0
  264.51    .016       0  308.84     .12       0
Bank Sta=239,254
XS Rating Curve= 0 ,0
Exp/Cntr=0.3,0.1

Type RM Length L Ch R = 1 ,2932.1  ,154.9,153.8,151.8
XS GIS Cut Line= 2
     1971689.412      230058.878     1971408.127      229861.773
#Sta/Elev= 30
       0 1863.23    16.4 1852.87    29.4 1840.74    39.2 1833.35    52.3 1824.58
    55.6 1822.57    75.2 1812.48    91.6 1804.48   104.7 1794.06   114.5 1785.22
   117.8 1783.27     121 1782.15   130.8 1780.53   140.7 1780.08   147.2 1780.52
     157 1783.02   173.4 1784.16   179.9 1785.48   186.5  1786.1   202.8 1784.71
  218.56 1784.95   222.4 1784.79   235.5 1785.82   238.8 1786.45   251.9 1790.64
  261.72 1792.71   287.9 1800.88   307.5  1808.9   327.1  1820.5   343.5  1832.2
#Mann= 5 ,-1 , 0
       0     .12       0   130.8    .045       0   147.2     .12       0
  218.56    .016       0  261.72     .12       0
Bank Sta=130.8,147.2
XS Rating Curve= 0 ,0
Exp/Cntr=0.3,0.1

Type RM Length L Ch R = 1 ,2778.2  ,219.9,223.3,226.6
XS GIS Cut Line= 2
     1971753.137      229913.027     1971487.354      229754.205
#Sta/Elev= 30
       0  1841.2     9.8 1836.99    26.1 1828.15    52.2 1815.37    61.9 1811.54
      75 1807.36    81.5 1806.06      88 1803.41   104.3 1795.23   120.6 1785.66
   133.6 1778.99   142.7 1778.07   157.7 1777.84   159.7 1777.82     163 1777.91
   169.5 1779.28   185.8 1779.72  191.11  1780.6   198.8    1782   205.3 1785.13
   208.6 1786.21   221.6 1787.12   231.4 1789.18   241.2 1791.83     251  1795.4
   257.5 1798.76   273.8  1809.2   283.6 1816.17   290.1 1821.38   309.6  1835.4
#Mann= 4 ,-1 , 0
       0     .12       0   142.7    .045       0   157.7    .016       0
  191.11     .12       0
Bank Sta=142.7,157.7
XS Rating Curve= 0 ,0
Exp/Cntr=0.3,0.1

Type RM Length L Ch R = 1 ,2554.9  ,217.1,225.1,232.5
XS GIS Cut Line= 2
     1971864.363      229749.254       1971637.5      229564.925
#Sta/Elev= 30
       0 1839.76    22.7 1825.87    32.5 1819.19    48.7 1810.08    58.5 1803.84
    84.4 1784.93   100.7 1775.16   107.2 1768.29   110.4 1766.15   116.9  1763.2
   121.1 1762.37   133.2 1762.14   136.1 1762.14  140.51 1762.29   142.9  1762.6
   146.2 1764.84   152.6 1770.68   155.9 1772.12   162.4 1773.06  181.85 1774.17
   191.6 1774.19   201.4 1775.12   204.6 1775.99   211.1 1779.01   220.8 1779.95
   227.4 1781.78   240.3 1788.12   259.8 1799.46   276.1 1807.63   292.3 1817.33
#Mann= 5 ,-1 , 0
       0     .12       0   121.1    .045       0   136.1     .12       0
  140.51    .016       0  181.85     .12       0
Bank Sta=121.1,136.1
XS Rating Curve= 0 ,0
Exp/Cntr=0.3,0.1

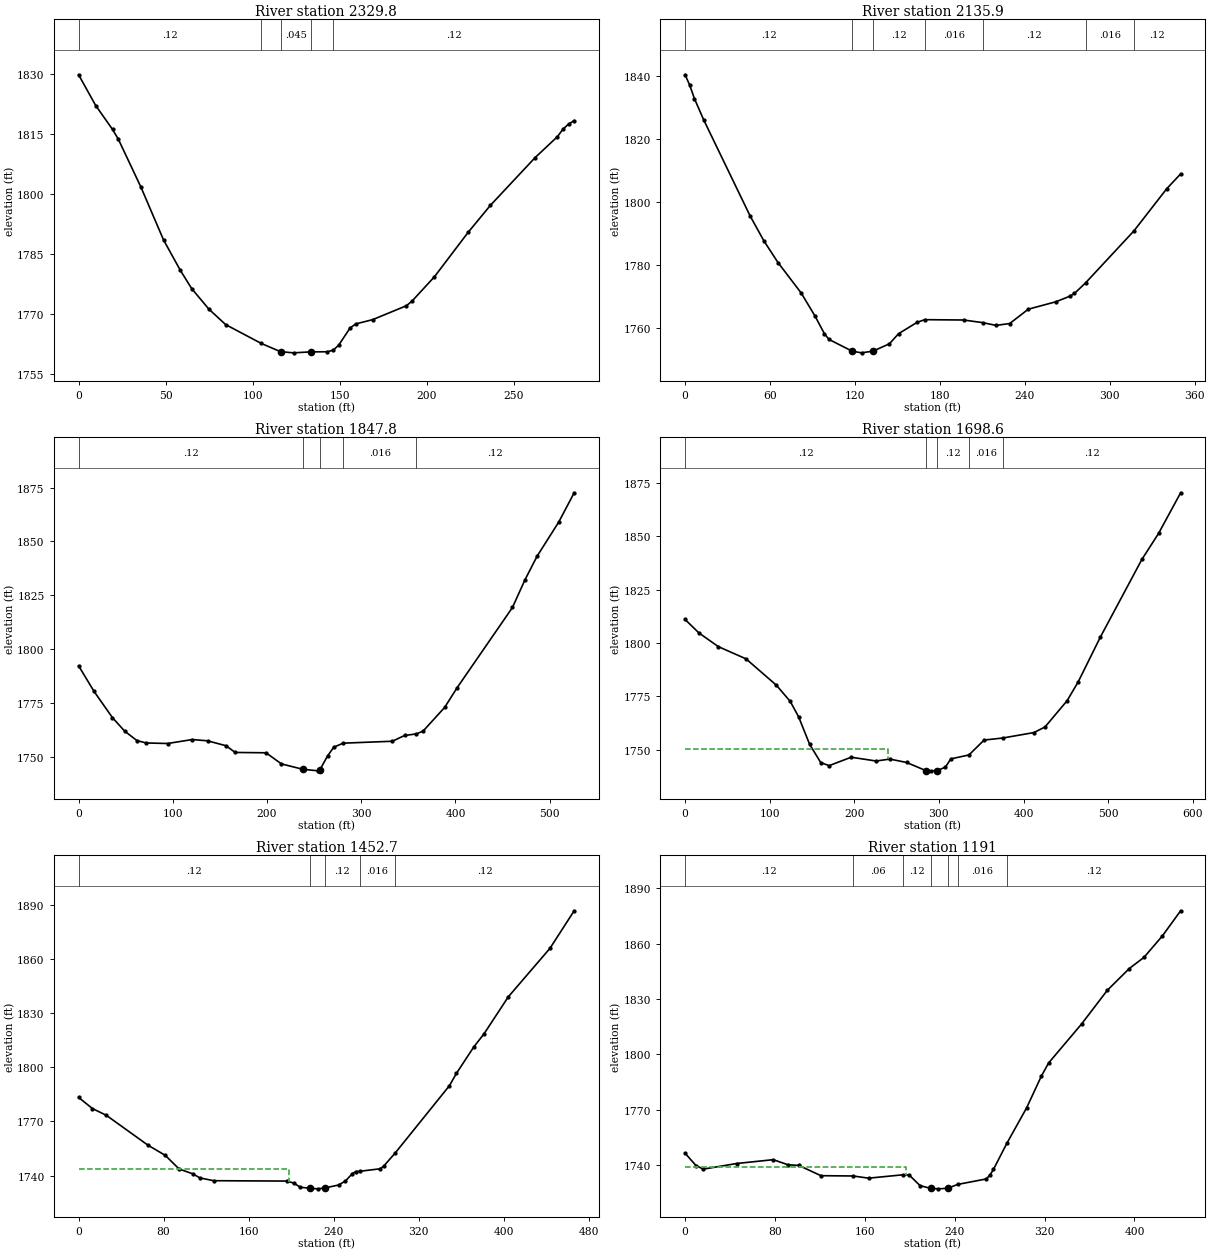
Type RM Length L Ch R = 1 ,2329.8  ,188.4,194,198.7
XS GIS Cut Line= 3
     1971971.702      229605.724      1971878.82      229452.946
     1971797.223      229385.238
#Sta/Elev= 30
       0 1829.88     9.8 1822.18    19.5 1816.17    22.8 1813.75    35.8 1801.73
    48.8 1788.49    58.5 1780.83      65 1776.28    74.8 1771.17    84.5 1767.27
  104.95 1762.55  116.04 1760.48   123.5 1760.19   133.3 1760.43     143 1760.46
  146.39 1760.87   149.5 1762.14     156 1766.41   159.3 1767.44     169 1768.51
   188.4    1772   191.6 1773.15   204.5 1779.26   223.8 1790.36   236.6 1797.13
   262.3  1809.1   275.2 1814.38   278.4 1816.27   281.6 1817.53   284.8  1818.4
#Mann= 5 ,-1 , 0
       0     .12       0  104.95    .016       0  116.04    .045       0
   133.3    .016       0  146.39     .12       0
Bank Sta=116.04,133.3
XS Rating Curve= 0 ,0
Exp/Cntr=0.3,0.1

Type RM Length L Ch R = 1 ,2135.9  ,299,288.1,276
XS GIS Cut Line= 3
     1972119.596      229540.527     1972058.001      229353.688
     1971938.917      229257.189
#Sta/Elev= 30
       0 1840.34     3.3    1837     6.6 1832.75    13.1 1826.05    45.9  1795.5
    55.7 1787.53    65.6 1780.69      82    1771    91.8 1763.64    98.4 1758.06
   101.6 1756.26     118 1752.52   124.6 1751.99  132.79 1752.54   144.3 1754.86
   150.8 1758.08   163.9 1761.69  169.29 1762.53   196.7 1762.42  210.19 1761.59
   219.6 1760.71   229.3  1761.3   242.4 1765.86     262 1768.23   271.7 1769.98
     275 1770.86  282.83 1774.21  317.02 1790.74   340.2 1804.15     350 1808.84
#Mann= 7 ,-1 , 0
       0     .12       0     118    .045       0  132.79     .12       0
  169.29    .016       0  210.19     .12       0  282.83    .016       0
  317.02     .12       0
Bank Sta=118,132.79
XS Rating Curve= 0 ,0
Exp/Cntr=0.3,0.1

Type RM Length L Ch R = 1 ,1847.8  ,168.4,149.2,129.2
XS GIS Cut Line= 4
     1972288.939      229395.702     1972266.354      229237.608
     1972122.632      229104.152     1971954.271      229079.514
#Sta/Elev= 30
       0 1792.27    16.3 1780.47    35.8 1768.31    48.9 1761.98    61.9 1757.62
    71.7 1756.51    94.5 1756.26   120.6  1758.1   136.9  1757.5   156.4 1755.23
   166.2 1752.11   198.9 1751.95   215.3 1746.79   238.2 1744.28   254.5 1743.58
   256.2 1744.17   264.3 1750.54   270.8 1754.53  280.67 1756.41     333 1757.31
     346 1759.98  358.47 1760.71   365.6    1762   388.6 1773.04   401.6 1782.04
   460.5 1819.36   473.6 1832.03   486.7 1843.19   509.6 1858.96     526 1872.56
#Mann= 5 ,-1 , 0
       0     .12       0   238.2    .045       0   256.2     .12       0
  280.67    .016       0  358.47     .12       0
Bank Sta=238.2,256.2
XS Rating Curve= 0 ,0
Exp/Cntr=0.3,0.1

Type RM Length L Ch R = 1 ,1698.6  ,246.2,245.8,245.5
XS GIS Cut Line= 2
     1972539.197      229007.309       1971957.6      229076.754
#Sta/Elev= 30
       0 1811.02    16.4  1804.7    39.3 1798.29      72 1792.57     108 1780.17
   124.3  1772.6   134.2 1765.36   147.2 1752.49   160.3 1743.96   170.2  1742.5
   196.3 1746.45   225.8 1744.68   242.1 1745.58   261.8 1743.99   284.7 1740.16
   291.2 1740.07   297.8 1740.18   307.6 1741.78   314.1 1745.67   335.5 1747.52
   353.4  1754.5  375.46 1755.46   412.3 1758.01   425.4 1760.64   451.6 1772.99
   464.7 1781.84   490.8 1802.76   539.9 1839.18   559.6 1851.35   585.7 1870.42
#Mann= 5 ,-1 , 0
       0     .12       0   284.7    .045       0   297.8     .12       0
   335.5    .016       0  375.46     .12       0
#XS Ineff= 2 , 0
          239.63 1750.17
Permanent Ineff=
       F       F
Bank Sta=284.7,297.8
XS Rating Curve= 0 ,0
Exp/Cntr=0.3,0.1

Type RM Length L Ch R = 1 ,1452.7  ,267.8,261.7,255.2
XS GIS Cut Line= 2
     1972447.531      228766.945     1971985.291      228829.879
#Sta/Elev= 30
       0 1783.26      13 1777.11    26.1 1773.36    65.2 1756.87    81.6 1751.19
    94.6 1743.65   107.6 1740.96   114.2 1738.71   127.2 1737.18   195.7 1736.98
   202.3 1735.93   208.8 1733.54   217.9 1733.02   225.1 1732.68   231.6 1733.17
   244.7 1734.78   251.2 1737.03   257.7 1741.12     261 1742.25  264.92 1742.41
   283.8 1743.78   287.1 1745.18  297.75 1752.33   349.1 1789.78   355.6 1796.53
   371.9 1811.12   381.7 1818.52   404.5 1838.95   443.7 1865.77   466.5 1886.56
#Mann= 5 ,-1 , 0
       0     .12       0   217.9    .045       0   231.6     .12       0
  264.92    .016       0  297.75     .12       0
#XS Ineff= 2 , 0
          197.63 1743.41
Permanent Ineff=
       F       F
Bank Sta=217.9,231.6
XS Rating Curve= 0 ,0
Exp/Cntr=0.3,0.1

Type RM Length L Ch R = 1 ,1191    ,267.3,264.6,262
XS GIS Cut Line= 2
     1972358.555      228458.785     1971954.909      228636.736
#Sta/Elev= 30
       0 1746.29     9.8 1739.55    16.3 1737.68    45.8 1740.72    78.4  1742.8
    91.5 1740.07   101.3 1739.67   120.9 1734.12  149.43 1733.96   163.4 1732.78
   193.7 1734.59   199.3 1734.57   209.1 1728.75   218.7 1727.22   225.5 1726.99
   233.7  1727.3  242.72  1729.4     268 1732.34   271.2 1734.28   274.5 1737.55
  286.46 1751.74   303.9 1770.78     317 1787.95   323.5 1795.19   352.9 1816.35
   375.8 1834.62   395.4 1846.45   408.4 1852.47   424.8 1864.09   441.1 1877.76
#Mann= 7 ,-1 , 0
       0     .12       0  149.43     .06       0   193.7     .12       0
   218.7    .045       0   233.7     .12       0  242.72    .016       0
  286.46     .12       0
#XS Ineff= 2 , 0
          196.59 1738.92
Permanent Ineff=
       F       F
Bank Sta=218.7,233.7
XS Rating Curve= 0 ,0
Exp/Cntr=0.3,0.1

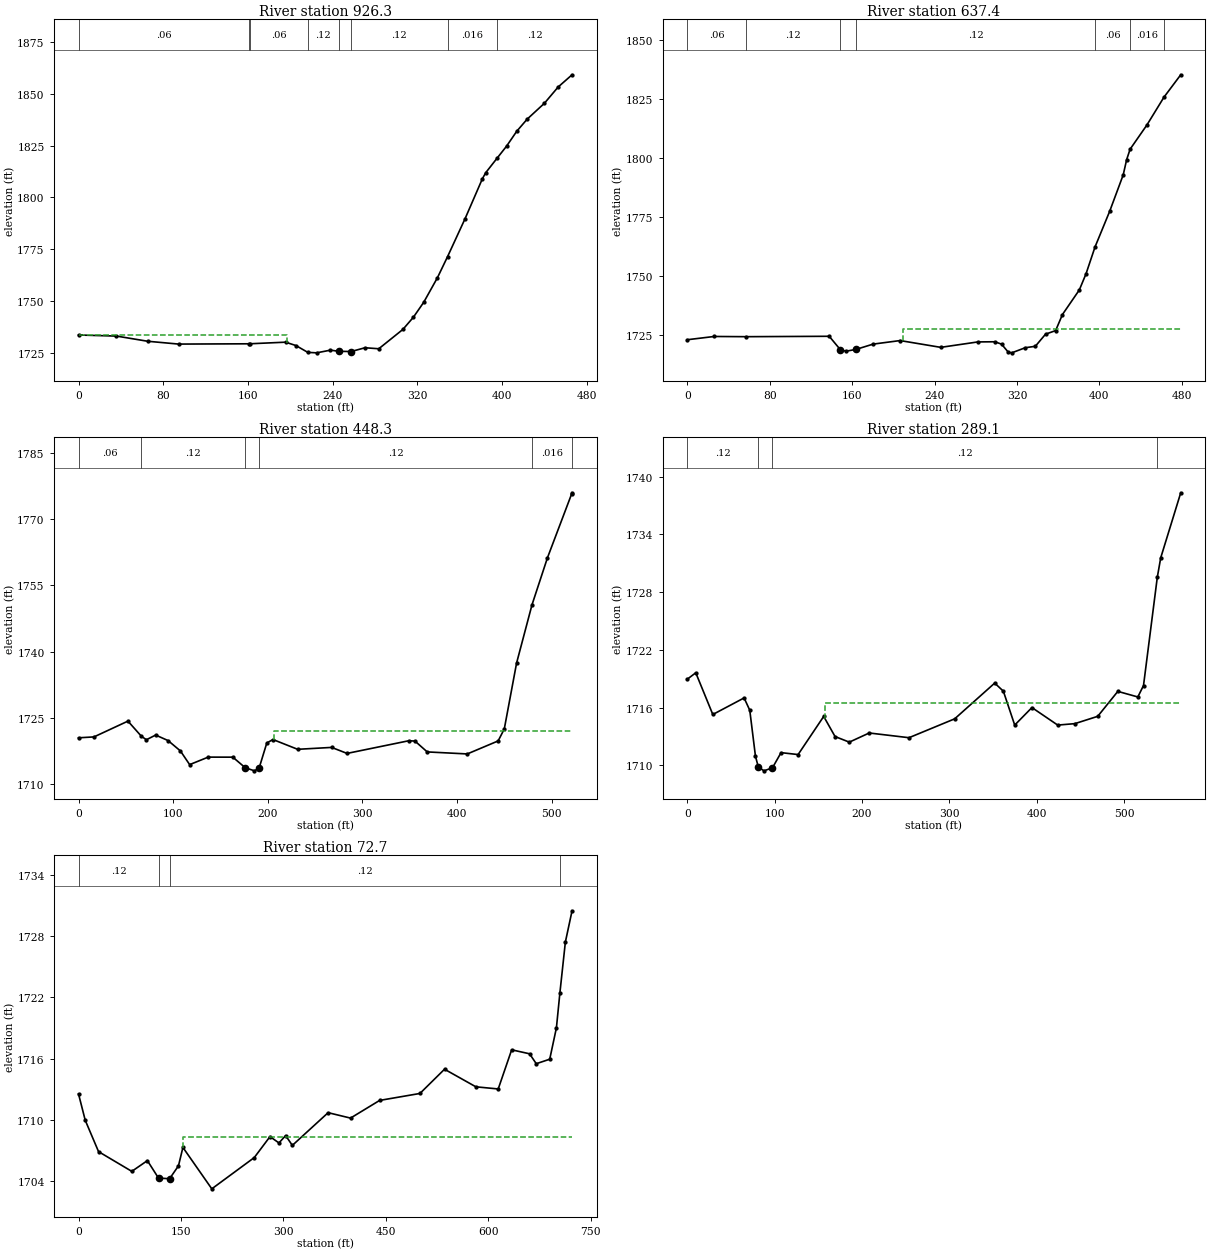
Type RM Length L Ch R = 1 ,926.3   ,300,288.9,276.5
XS GIS Cut Line= 2
     1972247.878      228187.517     1971846.402      228424.063
#Sta/Elev= 30
       0 1733.46    35.8 1732.94    65.2 1730.44    94.5 1729.07  160.97 1729.21
  161.77 1729.22   195.5 1729.99   205.3 1728.36  216.45 1725.07   224.8 1724.84
   237.9 1726.14   245.8 1725.58   257.4 1725.47   270.5  1727.3   283.5 1726.81
   306.3 1736.17   316.1 1741.99   325.9 1749.23   338.9 1761.15  348.48 1771.35
     365 1789.67   381.3 1808.91   384.5 1811.87  395.04 1818.77   404.1 1824.64
   413.8  1831.9   423.6 1837.73   439.9 1845.41   452.9 1853.28     466 1859.17
#Mann= 8 ,-1 , 0
       0     .06       0  160.97     .12       0  161.77     .06       0
  216.45     .12       0   245.8    .045       0   257.4     .12       0
  348.48    .016       0  395.04     .12       0
#XS Ineff= 2 , 0
          197.11 1733.24
Permanent Ineff=
       F       F
Bank Sta=245.8,257.4
XS Rating Curve= 0 ,0
Exp/Cntr=0.3,0.1

Type RM Length L Ch R = 1 ,637.4   ,183.6,189.1,193.7
XS GIS Cut Line= 2
     1972022.183      227914.557     1971783.902      228329.922
#Sta/Elev= 30
       0 1723.17    26.2 1724.55   57.21 1724.46   137.8 1724.63   148.7 1718.91
   154.2 1718.33   163.7 1719.07   180.4 1721.32   206.6 1722.82     246 1719.95
   282.1 1722.25   298.5 1722.31     305 1721.31   311.6 1717.89   314.9 1717.63
     328 1719.79   337.8  1720.4   347.7 1725.52   357.5 1727.04   364.1 1733.82
   380.5 1744.24     387 1751.06  395.72  1762.4     410 1777.55   423.1 1792.92
   426.4 1799.32  429.77 1803.75   446.1    1814  462.66 1825.77   478.9 1835.22
#Mann= 7 ,-1 , 0
       0     .06       0   57.21     .12       0   148.7    .045       0
   163.7     .12       0  395.72     .06       0  429.77    .016       0
  462.66     .06       0
#XS Ineff= 2 , 0
                          209.49         1727.67
Permanent Ineff=
       F       F
Bank Sta=148.7,163.7
XS Rating Curve= 0 ,0
Exp/Cntr=0.3,0.1

Type RM Length L Ch R = 1 ,448.3   ,156,159.2,161.5
XS GIS Cut Line= 3
     1971906.298      227832.526     1971673.577      228083.648
      1971681.03      228262.552
#Sta/Elev= 30
       0 1720.46    16.3 1720.66    52.2 1724.24   66.431720.801    71.7 1720.02
    81.5 1721.08    94.6 1719.83   107.6 1717.49   117.4 1714.38     137 1716.08
     163 1716.07   176.1 1713.68   185.9 1712.97  190.83 1713.63   198.9 1719.28
   205.4 1720.07   231.5 1717.85   267.4 1718.28   283.7 1716.92   348.9 1719.79
   355.4 1719.72   368.4 1717.26   410.7  1716.8   443.3 1719.75   449.8 1722.46
   462.8 1737.41  479.081750.606   495.4 1761.26  520.821775.661   521.4    1776
#Mann= 6 ,-1 , 0
       0     .06       0   66.43     .12       0   176.1    .045       0
  190.83     .12       0  479.08    .016       0  520.82     .12       0
#XS Ineff= 2 , 0
                          206.81         1722.06
Permanent Ineff=
       F       F
Bank Sta=176.1,190.83
XS Rating Curve= 0 ,0
Exp/Cntr=0.3,0.1

Type RM Length L Ch R = 1 ,289.1   ,210,216.4,221.7
XS GIS Cut Line= 3
     1971817.756      227760.912      1971603.31       227940.77
      1971606.16       228225.66
#Sta/Elev= 30
       0 1718.95     9.8 1719.62    29.3 1715.29    65.1 1717.01    71.6 1715.73
    78.1 1710.96    81.4 1709.83    87.9 1709.44    97.6 1709.76   107.4 1711.33
   126.9 1711.13   156.2 1715.09   169.2    1713   185.5 1712.42   208.3 1713.37
   253.8 1712.88   306.1 1714.84   351.9 1718.55   361.8 1717.71   374.8 1714.19
   394.5 1716.01     424 1714.19   443.6 1714.34   469.8  1715.1   492.8 1717.69
   515.7 1717.11   522.2  1718.3  537.991729.544   541.9 1731.56   564.8 1738.31
#Mann= 4 ,-1 , 0
       0     .12       0    81.4    .045       0    97.6     .12       0
  537.99    .016       0
#XS Ineff= 2 , 0
                          157.89         1716.47
Permanent Ineff=
       F       F
Bank Sta=81.4,97.6
XS Rating Curve= 0 ,0
Exp/Cntr=0.3,0.1

Type RM Length L Ch R = 1 ,72.7    ,70,72.7,75.4
XS GIS Cut Line= 3
     1971759.163      227594.245     1971583.381       227678.88
     1971569.268      228206.129
#Sta/Elev= 30
       0 1712.55     9.8 1709.98    29.3 1706.91      78 1704.98   100.8 1706.03
   117.1 1704.32   133.3 1704.26   146.3 1705.52   152.8 1707.32   195.1 1703.27
   257.3 1706.33   280.3 1708.38   293.4 1707.76   303.2 1708.48     313 1707.52
   365.4 1710.72   398.2 1710.19   440.8 1711.92   499.8  1712.6   535.8 1714.97
   581.7 1713.25   614.4 1713.04   634.1 1716.87   660.3 1716.48   670.1 1715.51
   689.8 1715.95   699.6 1719.02  704.731722.464   712.7 1727.41   722.5 1730.47
#Mann= 4 ,-1 , 0
       0     .12       0   117.1    .045       0   133.3     .12       0
  704.73    .016       0
#XS Ineff= 2 , 0
                          152.73         1708.34
Permanent Ineff=
       F       F
Bank Sta=117.1,133.3
XS Rating Curve= 0 ,0
Exp/Cntr=0.3,0.1

Chan Stop Cuts=-1
Use User Specified Reach Order=0
Composite Channel Slope=5